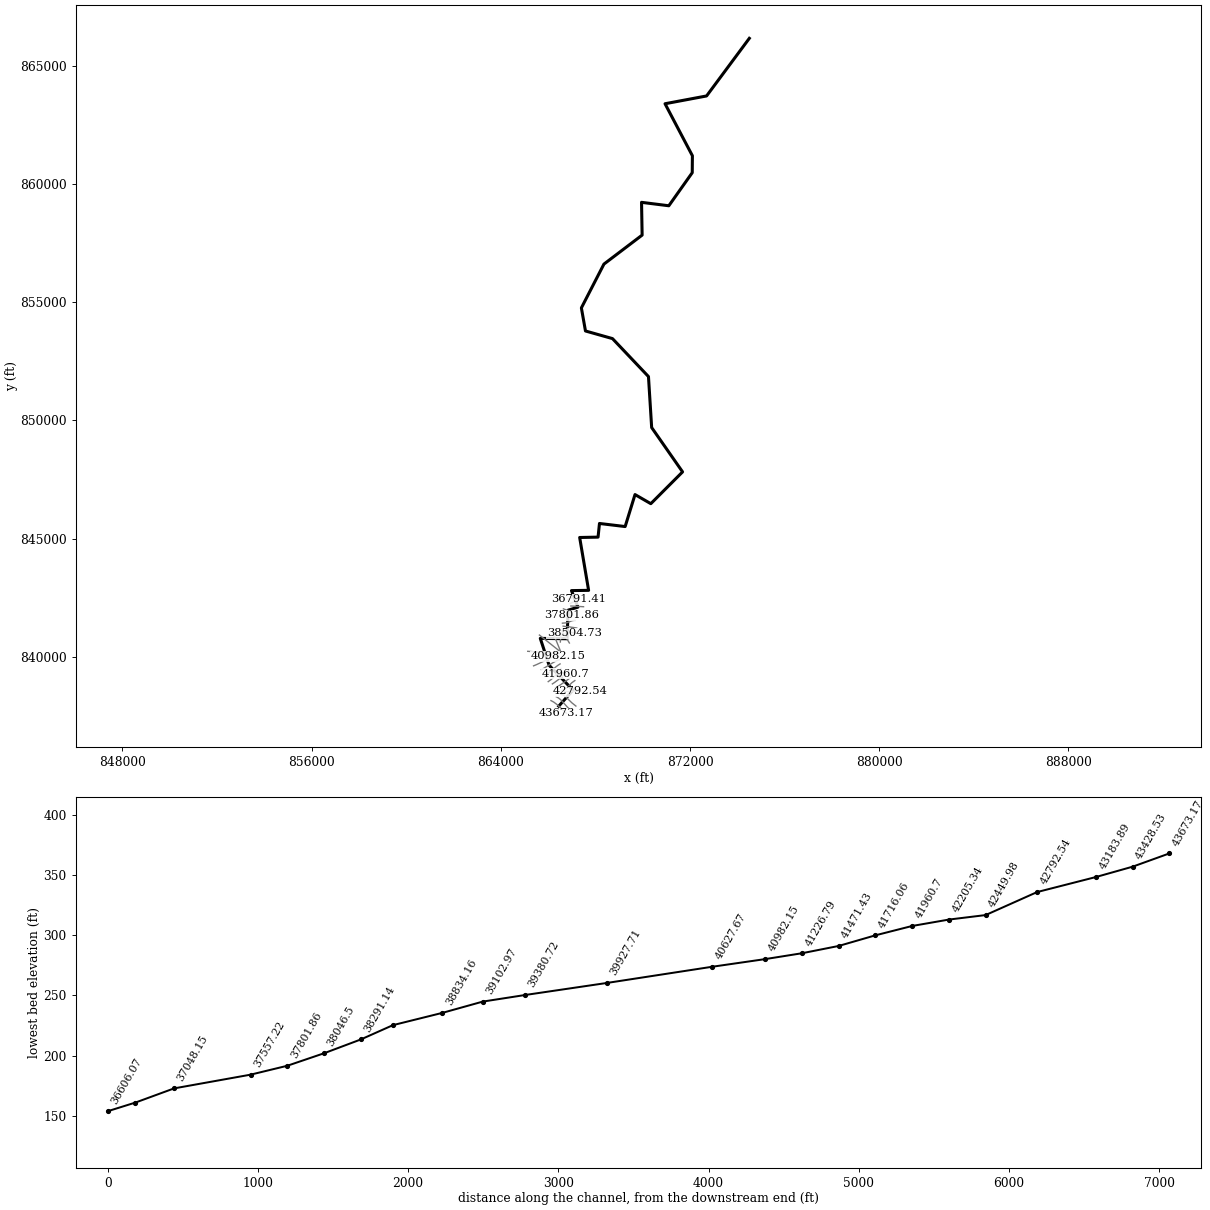
--- 16857_ras.prj (project) ---

Proj Title=16857
Current Plan=p01
Default Exp/Contr=0.3,0.1
English Units
Geom File=g01
Flow File=f01
Plan File=p01
Y Axis Title=Elevation
X Axis Title(PF)=Main Channel Distance
X Axis Title(XS)=Station
BEGIN DESCRIPTION:
RFD model 16857 exported to HEC-RAS
END DESCRIPTION:

--- 16857_ras.p01 (plan) ---

Plan Title=Plan 01
Program Version=4.10
Short Identifier=Plan 01
Geom File=g01
Flow File=f01
Subcritical Flow
Calc Critical at every XS
Secant Critical Depth

--- 16857_ras.f01 (steady flow) ---

Flow Title=Flow 01
Program Version=5.01
Number of Profiles= 6
Profile Names=10yr,25yr,50yr,100yr,100plus,500yr
River Rch & RM=16857,104,43673.17
11517.16 14750.717299.8119947.8624038.1526580.56
River Rch & RM=16857,104,43428.53
11530.2814768.3417320.7219971.9624067.1926611.42
River Rch & RM=16857,104,43183.89
11541.8514783.8817339.1519993.2124092.7926638.61
River Rch & RM=16857,104,42792.54
11843.6115189.8217820.4520548.0224761.3727348.61
River Rch & RM=16857,104,42449.98
11857.0615207.9417841.9320572.7924791.2127380.28
River Rch & RM=16857,104,42205.34
11863.0415215.9917851.4720583.7824804.4627394.35
River Rch & RM=16857,104, 41960.7
11869.7615225.03 17862.220596.1524819.3627410.16
River Rch & RM=16857,104,41716.06
 11876.115233.5717872.3220607.8224833.4327425.09
River Rch & RM=16857,104,41471.43
11963.7515351.5918012.2820769.1525027.8427631.38
River Rch & RM=16857,104,41226.79
11973.7315365.0318028.2220787.5325049.9927654.87
River Rch & RM=16857,104,40982.15
11981.8515375.97 18041.220802.4925068.02   27674
River Rch & RM=16857,104,40627.67
11991.8215389.3918057.1220820.8425090.1327697.45
River Rch & RM=16857,104,39927.71
12232.5115713.7618441.8621264.3425624.5628264.17
River Rch & RM=16857,104,39380.72
12266.36 15759.418495.9921326.7425699.7728343.88
River Rch & RM=16857,104,39102.97
12567.3916165.5618977.8821882.2226369.1529052.96
River Rch & RM=16857,104,38834.16
12575.4316176.4218990.7621897.0726387.0429071.91
River Rch & RM=16857,104,38504.73
12592.8916199.9919018.7421929.32 26425.929113.05
River Rch & RM=16857,104,38291.14
12598.82   1620819028.2421940.28 26439.129127.02
River Rch & RM=16857,104, 38046.5
12605.0916216.4819038.2921951.8726453.0729141.81
River Rch & RM=16857,104,37801.86
12629.1216248.9219076.7921996.2426506.5529198.42
River Rch & RM=16857,104,37557.22
 12639.916263.4719094.0622016.1526530.5429223.81
River Rch & RM=16857,104,37048.15
12760.8616426.8619287.9722239.6726799.8829508.86
River Rch & RM=16857,104,36791.41
12762.9216429.6519291.2722243.4826804.4829513.73
River Rch & RM=16857,104,36606.07
12776.6616448.21 19313.322268.8726835.08 29546.1
River Rch & RM=16857,104,   36267
12780.7816453.7819319.9122276.4826844.2529555.81
River Rch & RM=16857,104,36050.01
12784.8916459.3419326.51 22284.126853.4329565.51
River Rch & RM=16857,104,35844.76
12787.2916462.5819330.3622288.5426858.7729571.17
River Rch & RM=16857,104,35771.28
12792.0916469.0719338.0622297.4126869.4629582.49
River Rch & RM=16857,104,35552.34
12804.77 16486.219358.3922320.8426897.7129612.36
River Rch & RM=16857,104,35272.93
12809.5616492.6819366.0822329.7126908.3829623.66
River Rch & RM=16857,104,35023.76
12814.0116498.6919373.2122337.9326918.2929634.15
River Rch & RM=16857,104,34774.58
12822.2216509.7819386.38 22353.126936.5829653.49
River Rch & RM=16857,104,34525.41
12862.8316564.6619451.52 22428.227027.0729749.21
River Rch & RM=16857,104,34276.24
12871.6816576.6319465.7222444.57 27046.829770.08
River Rch & RM=16857,104,34027.06
12884.2716593.6519485.9222467.8527074.8529799.76
River Rch & RM=16857,104,33777.89
12886.9916597.3219490.2822472.8827080.9129806.16
River Rch & RM=16857,104,33528.72
12893.7916606.5119501.1922485.4527096.0629822.19
River Rch & RM=16857,104,32951.15
12903.9716620.2819517.5322504.2927118.77 29846.2
River Rch & RM=16857,104,32273.42
12914.8316634.9619534.9522524.3727142.9729871.79
River Rch & RM=16857,104,31510.76
 14816.419214.6722599.4326056.7531399.6634360.51
River Rch & RM=16857,104,31312.36
14817.5619216.2522601.3126058.9231402.2734363.25
River Rch & RM=16857,104,31010.57
14898.84 19326.922732.8526210.5431584.9834555.37
River Rch & RM=16857,104,30827.98
14900.5719329.2622735.6626213.7731588.8834559.46
River Rch & RM=16857,104,30557.65
14906.0519336.7122744.5226223.9931601.1934572.41
River Rch & RM=16857,104,30289.47
14947.7719393.5222812.0626301.8531695.0134671.03
River Rch & RM=16857,104,30040.29
 14992.819454.8522884.9726385.8831796.2734777.48
River Rch & RM=16857,104,29791.12
14995.3819458.3522889.1426390.6931802.0734783.57
River Rch & RM=16857,104,29541.95
15001.6719466.9322899.3426402.4431816.2334798.45
River Rch & RM=16857,104,29292.77
15006.2519473.1622906.7526410.9931826.5334809.28
River Rch & RM=16857,104,29079.66
 15013.4 19482.922918.3326424.3331842.6134826.17
River Rch & RM=16857,104,28742.62
 15025.419499.2422937.7626446.73 31869.634854.55
River Rch & RM=16857,104,28483.12
15031.3919507.4122947.4726457.9331883.0934868.72
River Rch & RM=16857,104,28296.08
15033.6819510.5222951.1726462.1931888.2334874.13
River Rch & RM=16857,104,28046.91
15048.5119530.73 22975.226489.88 31921.6 34909.2
River Rch & RM=16857,104,27905.98
15055.0719539.6622985.8126502.1231936.3534924.69
River Rch & RM=16857,104,27792.11
15062.1919549.3622997.3526515.4231952.3734941.54
River Rch & RM=16857,104,27552.49
15066.1819554.7923003.8126522.8631961.3434950.96
River Rch & RM=16857,104,27312.86
15079.5519573.0123025.4726547.8331991.4434982.58
River Rch & RM=16857,104,27073.24
15083.8219578.8223032.38 26555.832001.0434992.67
River Rch & RM=16857,104,26996.84
15086.9519583.0823037.4526561.6432008.0735000.06
River Rch & RM=16857,104,26756.03
15090.0719587.3523042.5226567.4832015.1135007.46
River Rch & RM=16857,104,26515.22
17770.18 23253.927406.4131597.4338076.4541354.52
River Rch & RM=16857,104,26274.41
17773.2523258.1227411.4331603.2238083.42 41361.8
River Rch & RM=16857,104,26038.18
17787.6423277.8927434.9831630.3638116.1341395.93
River Rch & RM=16857,104, 25792.8
17808.8623307.0227469.6931670.3738164.3441446.25
River Rch & RM=16857,104,25551.99
17813.5723313.49 27477.431679.2538175.0441457.42
River Rch & RM=16857,104,25247.76
17818.7423320.6127485.8731689.0238186.81 41469.7
River Rch & RM=16857,104,24869.65
17822.2823325.4627491.6531695.6838194.8441478.08
River Rch & RM=16857,104,24557.41
17931.3223475.2727670.13 31901.438442.7441736.75
River Rch & RM=16857,104,24347.96
18104.7223713.5827954.0732228.6638837.1142148.11
River Rch & RM=16857,104,24107.15
18107.0323716.7627957.8632233.0238842.37 42153.6
River Rch & RM=16857,104,23866.35
 18113.523725.6627968.4632245.2438857.0942168.95
River Rch & RM=16857,104,23625.54
18129.4323747.5627994.5532275.3238893.3442206.75
River Rch & RM=16857,104,23384.73
18134.0523753.9128002.1232284.0438903.8442217.71
River Rch & RM=16857,104,23143.92
18142.3523765.3328015.7232299.7238922.7342237.41
River Rch & RM=16857,104,22903.12
 18147.223771.9828023.6532308.8638933.76 42248.9
River Rch & RM=16857,104,22662.31
18153.1923780.2228033.4732320.1838947.3942263.13
River Rch & RM=16857,104, 22421.5
18159.4123788.7828043.6632331.9338961.5542277.89
River Rch & RM=16857,104, 22180.7
18180.8223818.2228078.7432372.3639010.2742328.69
River Rch & RM=16857,104,21939.89
18184.2723822.96 28084.432378.8839018.1342336.88
River Rch & RM=16857,104,21699.08
18197.3823840.9828105.8732403.6339047.9542367.98
River Rch & RM=16857,104,21458.28
18200.3623845.0928110.7632409.2739054.7542375.06
River Rch & RM=16857,104,21217.47
18201.5123846.6728112.6532411.4439057.3642377.79
River Rch & RM=16857,104,20976.66
18241.2123901.27 28177.732486.4239147.72   42472
River Rch & RM=16857,104,20479.49
18317.5924006.3128302.8832630.6939321.5842653.25
River Rch & RM=16857,104,19663.11
18345.8524045.1928349.2132684.0939385.9342720.32
River Rch & RM=16857,104,19481.93
18347.4424047.3828351.8232687.1139389.56 42724.1
River Rch & RM=16857,104,19210.21
18351.3124052.7128358.1632694.4239398.3742733.29
River Rch & RM=16857,104,17846.13
18384.9724099.0128413.3432758.0239475.0142813.16
River Rch & RM=16857,104,16890.43
28298.8538234.4446425.8951680.2375453.1452727.98
River Rch & RM=16857,104,16201.14
 28305.538249.4346448.89 51710.775497.6252765.78
River Rch & RM=16857,104,15380.78
28400.7138463.72 46777.352145.7976132.8653305.49
River Rch & RM=16857,104, 14548.9
28451.3338582.0746960.8952390.9276490.7453613.16
River Rch & RM=16857,104,13330.54
28481.21 38651.747068.8452535.0276701.1353793.95
River Rch & RM=16857,104,12385.62
28525.2138754.2147227.8252747.3277011.0954060.45
River Rch & RM=16857,104,11469.19
28533.75   3877547260.49 52791.3 77075.354116.33
River Rch & RM=16857,104,9894.968
 28836.4 39470.948337.11 54228.279173.1855917.58
River Rch & RM=16857,104,  9219.1
28842.5339485.9548360.8854260.3579220.1155958.68
River Rch & RM=16857,104,8220.817
30970.7243263.4753693.6660973.1689020.8263538.32
River Rch & RM=16857,104,6232.939
31389.1944163.9755069.5762804.6491694.7765802.23
River Rch & RM=16857,104,5091.234
31410.1344211.8155144.2462905.4591841.9565929.57
River Rch & RM=16857,104,2525.768
31508.1144438.0955498.7363385.2692542.4866538.09
River Rch & RM=16857,104, 1465.11
31536.8644505.3555604.5963528.98 92752.366721.19
River Rch & RM=16857,104,      -0
31631.7944729.2455957.9764009.7393454.2167335.58
Boundary for River Rch & Prof#=16857,104,1
Up Type= 0
Dn Type= 2
Boundary for River Rch & Prof#=16857,104,2
Up Type= 0
Dn Type= 2
Boundary for River Rch & Prof#=16857,104,2
Up Type= 0
Dn Type= 2
Boundary for River Rch & Prof#=16857,104,2
Up Type= 0
Dn Type= 2
Boundary for River Rch & Prof#=16857,104,2
Up Type= 0
Dn Type= 2
Boundary for River Rch & Prof#=16857,104,2
Up Type= 0
Dn Type= 2

--- 16857_ras.g01 (geometry) ---

Geom Title=16857
Program Version=4.10

River Reach=16857,104
Reach XY= 30
866449.213933776837914.460994639867052.328204464838591.109394797
866042.090755869839642.900292175865668.710418393840780.387399117
866798.629895755840764.743770709866846.661208508841973.240063502
867260.345500729842100.701193856866987.641039624842800.561884004
867712.082182289842811.636065232  867334.0640785845046.730336564
868111.387409851 845061.82997951868171.511562871845639.345850551
869257.321633283845509.113210971869674.519821375846861.947827987
 870342.28497248846476.327555003  871685.4434852847820.508711103
870378.263543348849695.162602838870243.314575125851851.701117491
868721.517267607853457.127018034867579.584742751 853779.39244419
867406.271566744854755.755340209868360.497700841856608.247513009
869975.042304244857833.284755334 869950.59913391859219.116392557
 871103.98689239859074.543067001872094.369254615 860472.68322665
 872100.90750169861189.328744106870943.647554231863388.621287956
872700.680268847863718.090091729874508.074596049866154.437521829

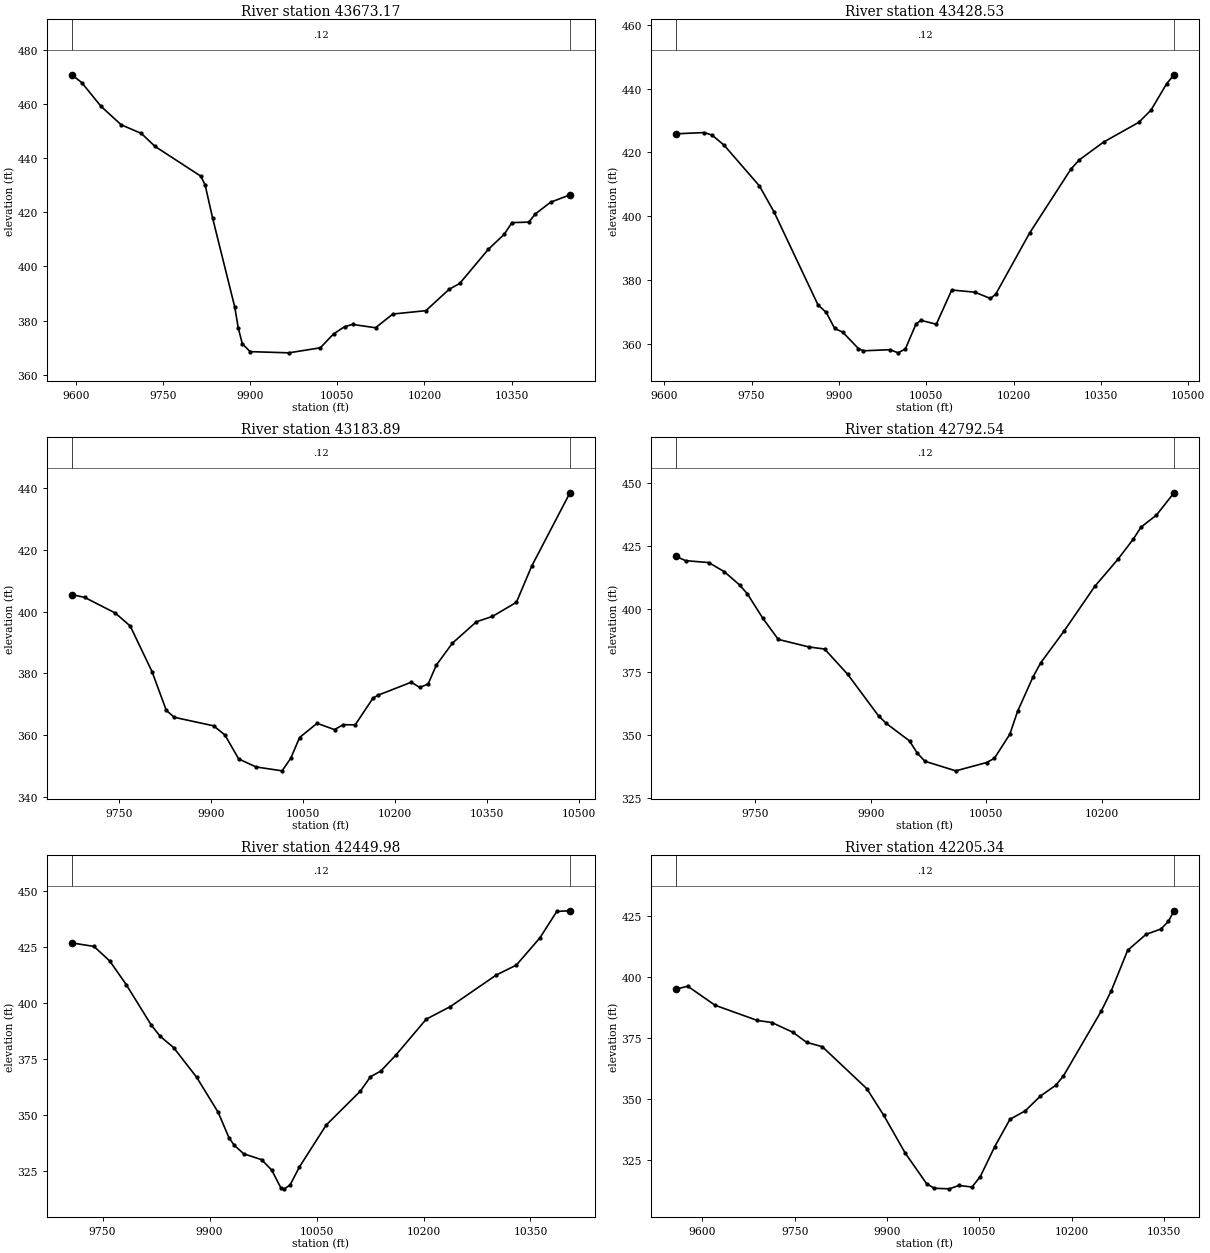
Type RM Length L Ch R = 1 ,43673.17,244.637600,244.637600,244.637600
XS GIS Cut Line= 6
866119.711316594 838149.61273401866236.870712874838086.383508526
 866362.69119654837992.646628296866450.626425737837914.530754668
866626.571039821837745.761726031866780.337545003837608.959291688
#Sta/Elev= 30
9593.148470.67759610.015467.81719643.432  459.01 9678.06452.21999712.689449.0464
9736.253444.25759815.136433.27019822.557430.0105 9835.31417.9173 9873.57384.9604
9879.587377.26269886.467371.50539899.841368.5457 9966.71368.098710020.92369.9622
10043.66375.082110062.49377.715210076.34378.582910115.89377.349410145.63382.4115
10202.56383.655510242.63 391.547 10260.8 393.68810310.25406.334310337.27 411.781
10350.79416.134810379.75416.321210391.04 419.34110417.33423.668810450.64426.3859
#Mann= 3 , 0 , 0
9593.148    0.12       09593.148    0.12       010450.64    0.12       0
#XS Ineff= 2 , 0
       0                               0
Bank Sta=9593.148,10450.64
Exp/Cntr=0.3,0.1

Type RM Length L Ch R = 1 ,43428.53,244.637700,244.637700,244.637700
XS GIS Cut Line= 6
866341.571735583838313.076971483866434.802801803838262.436802774
866516.287924037838199.008269024 866569.02206896838147.505421374
866819.568116211837869.424286124866964.703141592 837734.96972292
#Sta/Elev= 30
9620.189425.86549668.816426.25699682.126425.46859702.855422.29859763.531409.5082
9788.978401.22079864.096372.15599878.408369.7479 9892.72364.7652 9906.82363.5323
9933.749358.39269942.242357.70679987.606358.058410001.96357.0684 10014.4358.3284
10032.38366.0795 10040.9 367.28110067.41366.054510093.92376.805110133.68376.1158
10160.18374.152610169.24375.426710227.48394.6441 10298.6 414.78710313.11417.6924
10354.75423.267510415.07 429.45810436.15433.305410462.78441.5212 10475.7444.4061
#Mann= 3 , 0 , 0
9620.189    0.12       09620.189    0.12       0 10475.7    0.12       0
#XS Ineff= 2 , 0
       0                               0
Bank Sta=9620.189,10475.7
Exp/Cntr=0.3,0.1

Type RM Length L Ch R = 1 ,43183.89,391.346800,391.346800,391.346800
XS GIS Cut Line= 6
866545.224718726838418.584673992866638.790167808838382.852807477
866710.434183239 838336.56569703866774.930346191838279.783759196
866998.597821586838059.977126517867174.571352914837918.069058884
#Sta/Elev= 30
9673.413405.50129694.203404.58019744.052399.52659768.471395.31059803.959380.5621
9827.235 368.0299840.184365.78019904.224363.02529922.697360.07159945.161352.3063
9973.389349.7232 10015.9348.459110030.13352.589510044.36359.244210072.83363.8378
10101.29 361.80410115.53363.4016 10134.9 363.32810163.76371.924910171.42372.8702
10226.32377.138110240.04375.448310253.77376.539710267.08 382.65710293.22389.7488
10332.45396.6924 10358.6 398.43410397.52402.977810422.62 414.73910484.84438.4318
#Mann= 3 , 0 , 0
9673.413    0.12       09673.413    0.12       010484.84    0.12       0
#XS Ineff= 2 , 0
       09897.098                       0
Bank Sta=9673.413,10484.84
Exp/Cntr=0.3,0.1

Type RM Length L Ch R = 1 ,42792.54,342.566200,342.566200,342.566200
XS GIS Cut Line= 5
 866702.49106395838530.852742091866781.860916073 838534.12162262
866817.405620832838534.138945466866846.600705397838531.009965551
867347.784539869838547.114890501
#Sta/Elev= 30
9647.508421.07639660.027419.36749690.053418.60399710.069415.02049730.084409.7072
9740.084406.20659760.084396.54149780.185388.11889820.266385.09029840.276384.3052
9870.291374.22249910.312357.72269920.317354.76189950.333347.83499960.338343.0203
9970.343339.751210010.36335.962310050.38339.258110060.39340.9347 10080.4350.4789
 10090.4359.524110110.42373.195410120.42378.818210150.44391.301610190.46409.1286
10220.47419.886710240.48427.913410250.49432.6686 10270.5437.444710293.29446.3027
#Mann= 3 , 0 , 0
9647.508    0.12       09647.508    0.12       010293.29    0.12       0
#XS Ineff= 2 , 0
       0                               0
Bank Sta=9647.508,10293.29
Exp/Cntr=0.3,0.1

Type RM Length L Ch R = 1 ,42449.98,244.637700,244.637700,244.637700
XS GIS Cut Line= 6
866586.475713346838564.994837611866680.684259109838612.935934154
 866727.81081623838648.441169065866849.251779743838751.990073572
867002.642287013838904.705948523867130.554413779838996.160445813
#Sta/Elev= 30
9706.909426.69779737.853425.13649760.083418.60459783.168408.04539818.218390.0096
9830.739384.97819849.482379.97139881.767366.74089912.102 350.9969927.269 339.615
9934.582336.30599947.882332.49659972.983329.86829987.127325.22299999.957317.2945
10004.83316.844210012.92 318.57310025.91326.576110063.56345.350110111.33360.4501
10125.66366.928510139.99369.430610161.29376.6067 10203.8392.625710237.64398.2617
10302.14412.3697 10330.2   416.8 10363.2428.946110386.97440.796310405.38441.0552
#Mann= 3 , 0 , 0
9706.909    0.12       09706.909    0.12       010405.38    0.12       0
#XS Ineff= 2 , 0
       0                               0
Bank Sta=9706.909,10405.38
Exp/Cntr=0.3,0.1

Type RM Length L Ch R = 1 ,42205.34,244.637700,244.637700,244.637700
XS GIS Cut Line= 6
866287.690930957838682.998956591866358.933541316838717.222859506
866437.455328897838761.672218283866524.198209929838817.844716587
866878.251123416839070.080393464866962.667344425839127.207587139
#Sta/Elev= 30
9557.101 394.8699576.256396.06499620.669 388.2779689.076382.07279712.826381.2034
9747.272377.18989769.287373.10199794.927371.29369867.264354.10399894.669343.2296
9929.634327.73329964.795315.06319976.987313.333610001.36313.098810017.02314.4852
10038.03 313.83610051.48318.057510075.09330.390410099.81341.582110124.52345.0121
10149.23351.064610173.94355.454410186.29359.145610248.07385.852710264.45394.2232
10291.07410.784110320.89417.303510345.04419.479910357.12422.589510366.37426.9587
#Mann= 3 , 0 , 0
9557.101    0.12       09557.101    0.12       010366.37    0.12       0
#XS Ineff= 2 , 0
       0                               0
Bank Sta=9557.101,10366.37
Exp/Cntr=0.3,0.1

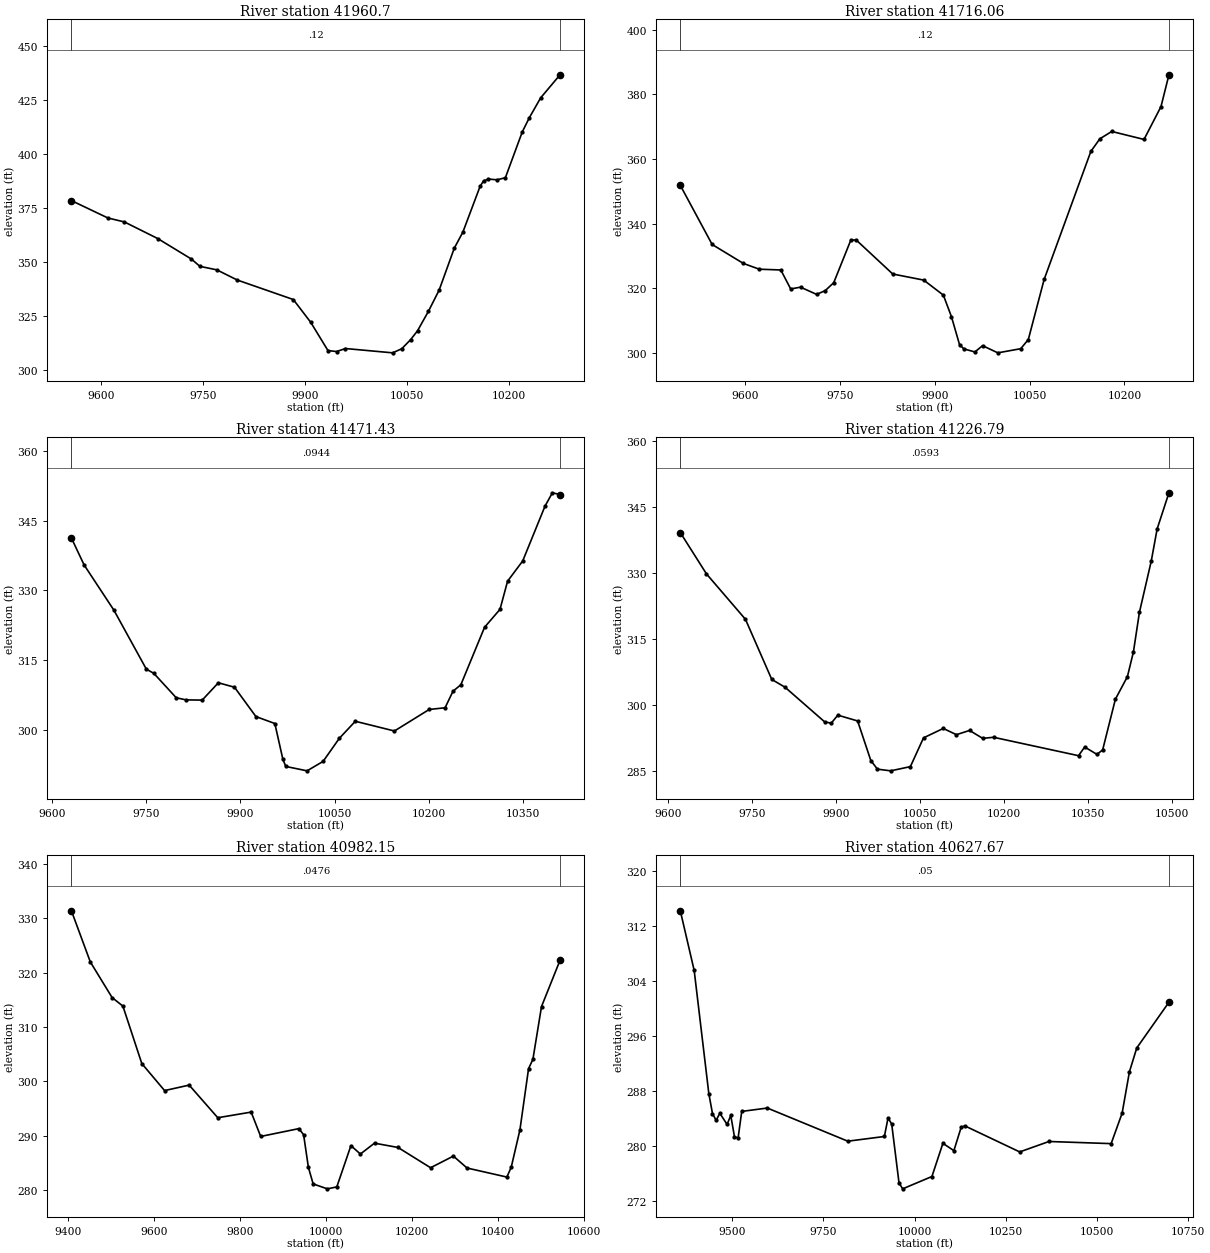
Type RM Length L Ch R = 1 , 41960.7,244.637600,244.637600,244.637600
XS GIS Cut Line= 6
866179.706880574838854.135645856 866274.00316733838916.730236994
866415.208531664839021.769585405866501.236422529839089.202810231
866593.297524213 839174.03950484866750.281533461839291.272181992
#Sta/Elev= 30
9555.939378.34239609.698370.28159633.959 368.4529682.998360.76639732.701 351.242
9745.164347.86639770.091346.2397 9800.28341.51799882.787332.48219908.396321.9315
9933.808308.82629946.514308.37869959.624309.773110029.03307.7746 10042.5309.6744
10055.64313.919610065.75318.007710081.84327.064510097.53336.839710119.86356.2865
10132.53363.7434 10157.8384.895210162.94387.480810170.24388.330410182.68387.9757
10195.11388.941910219.98410.171610230.22416.657910247.05425.958910275.65 436.663
#Mann= 3 , 0 , 0
9555.939    0.12       09555.939    0.12       010275.65    0.12       0
#XS Ineff= 2 , 0
       0                               0
Bank Sta=9555.939,10275.65
Exp/Cntr=0.3,0.1

Type RM Length L Ch R = 1 ,41716.06,244.637700,244.637700,244.637700
XS GIS Cut Line= 6
866003.440932116 838951.10857872866122.441102781 839037.23112234
866221.280231824839123.844806224866302.621108545839209.715310834
866450.740821942839406.976792353 866544.37488617839496.619672213
#Sta/Elev= 30
9497.203351.84149547.613333.53659597.023327.67069622.195325.88439656.272325.6472
9671.881319.77759687.489320.32189712.942  318.09 9726.48 319.2449740.019321.7017
9767.095334.89979775.598334.92449833.434 324.3969882.466322.51069913.532317.8601
9926.367311.18459939.202302.49499946.219301.2075 9963.45300.2691 9975.56302.2166
 9999.76299.996310036.02301.276510048.01304.120210073.06322.725210146.98362.3475
10161.28366.258610180.09368.516810231.13 366.05110257.99376.222310270.58386.0654
#Mann= 3 , 0 , 0
9497.203    0.12       09497.203    0.12       010270.58    0.12       0
#XS Ineff= 2 , 0
       0                               0
Bank Sta=9497.203,10270.58
Exp/Cntr=0.3,0.1

Type RM Length L Ch R = 1 ,41471.43,244.637700,244.637700,244.637700
XS GIS Cut Line= 6
865890.376742596839223.009201451865961.920340938839275.711535619
866215.709297276839480.868556247866338.693173441839583.618242458
866414.171514297839641.395010513866505.708662249839700.223671066
#Sta/Elev= 30
9630.377341.23639650.624335.44359698.216325.69899749.883313.03189761.806312.1301
9797.549306.8768 9813.28306.41899839.017306.37349864.754 310.0999890.491309.1407
9924.656  302.839954.833301.33669967.702293.61469972.322292.101310006.26291.1572
10031.87293.194610057.69298.151610083.22 301.819 10145.6299.725810201.02304.3558
10226.37304.722610238.97308.268810251.56309.678110289.34322.036510313.97 325.895
10326.05331.949610350.21336.309110385.81348.110310397.55350.966110409.76350.5801
#Mann= 3 , 0 , 0
9630.377  0.0944       09630.377  0.0944       010409.76  0.0944       0
#XS Ineff= 2 , 0
       0                10181.87       0
Bank Sta=9630.377,10409.76
Exp/Cntr=0.3,0.1

Type RM Length L Ch R = 1 ,41226.79,244.637700,244.637700,244.637700
XS GIS Cut Line= 6
 865714.71882687 839453.86540265866169.283464793839731.950001227
866250.683363888839778.866022823866323.473632932839816.693041063
 866386.67429408839845.048127586866475.175205034839875.761161881
#Sta/Elev= 30
9621.988339.25739668.692329.86369738.259319.54159785.214305.87059808.779304.1116
9879.474296.23899891.257295.92269903.039297.75299938.387296.43719961.952287.4283
9973.735285.4802  9997.3285.0961 10032.5286.052310055.98292.594410091.19294.7336
10114.66293.315310138.13294.2789 10161.5292.483310181.03292.722710332.55288.5399
10343.52  290.5110365.44288.8366 10375.6  289.8610398.32301.382510419.79306.5195
10430.51312.143510441.21321.138510462.27332.755710472.81340.085410493.88348.3064
#Mann= 3 , 0 , 0
9621.988  0.0593       09621.988  0.0593       010493.88  0.0593       0
#XS Ineff= 2 , 0
       09917.733        10380.31       0
Bank Sta=9621.988,10493.88
Exp/Cntr=0.3,0.1

Type RM Length L Ch R = 1 ,40982.15,354.477300,354.477300,354.477300
XS GIS Cut Line= 6
865384.429446374839618.686760383865493.654050575839664.098081668
866150.639220919839966.194548033866295.283606485 840010.08613578
866378.241798858840021.816409138866438.120463147840023.233100179
#Sta/Elev= 30
 9407.33331.39839451.267321.99049501.919315.43459527.098313.85339571.074303.2862
9624.057298.31139681.216299.32039747.763293.31599825.401294.35219847.583289.8695
9936.312291.31169947.404290.19499958.495284.19859969.586281.135610002.64280.2315
10024.57280.581110057.47 288.186 10079.4286.6347 10112.3288.634510166.97287.8448
10242.74284.113710295.78286.256610327.51284.062710420.15282.397710430.31 284.215
10450.52291.074510470.64302.3647 10480.7304.047310500.73313.770610543.88322.3014
#Mann= 3 , 0 , 0
 9407.33  0.0476       0 9407.33  0.0476       010543.88  0.0476       0
#XS Ineff= 2 , 0
       0 9929.87                       0
Bank Sta=9407.33,10543.88
Exp/Cntr=0.3,0.1

Type RM Length L Ch R = 1 ,40627.67,699.963000,699.963000,699.963000
XS GIS Cut Line= 2
865137.032445538840233.894103554866473.019358539840142.040684325
#Sta/Elev= 30
9358.042314.27499396.099305.59469436.193287.69499446.217284.7862 9456.24283.7876
9466.264284.82839486.311 283.2029496.335284.51599506.358281.44499516.382281.2023
9526.406285.09639596.571285.5866 9817.09280.76529917.326281.4509 9927.35284.1478
9937.374283.26519957.421274.69689967.444273.836710047.63275.6295 10077.7280.4568
10107.77279.390910127.82282.799510137.85282.9917 10288.2279.205410368.39280.7221
10538.79280.412210568.86284.842810588.91290.866610608.96294.323810697.18300.9759
#Mann= 3 , 0 , 0
9358.042    0.05       09358.042    0.05       010697.18    0.05       0
#XS Ineff= 2 , 0
       09923.872        10572.54       0
Bank Sta=9358.042,10697.18
Exp/Cntr=0.3,0.1

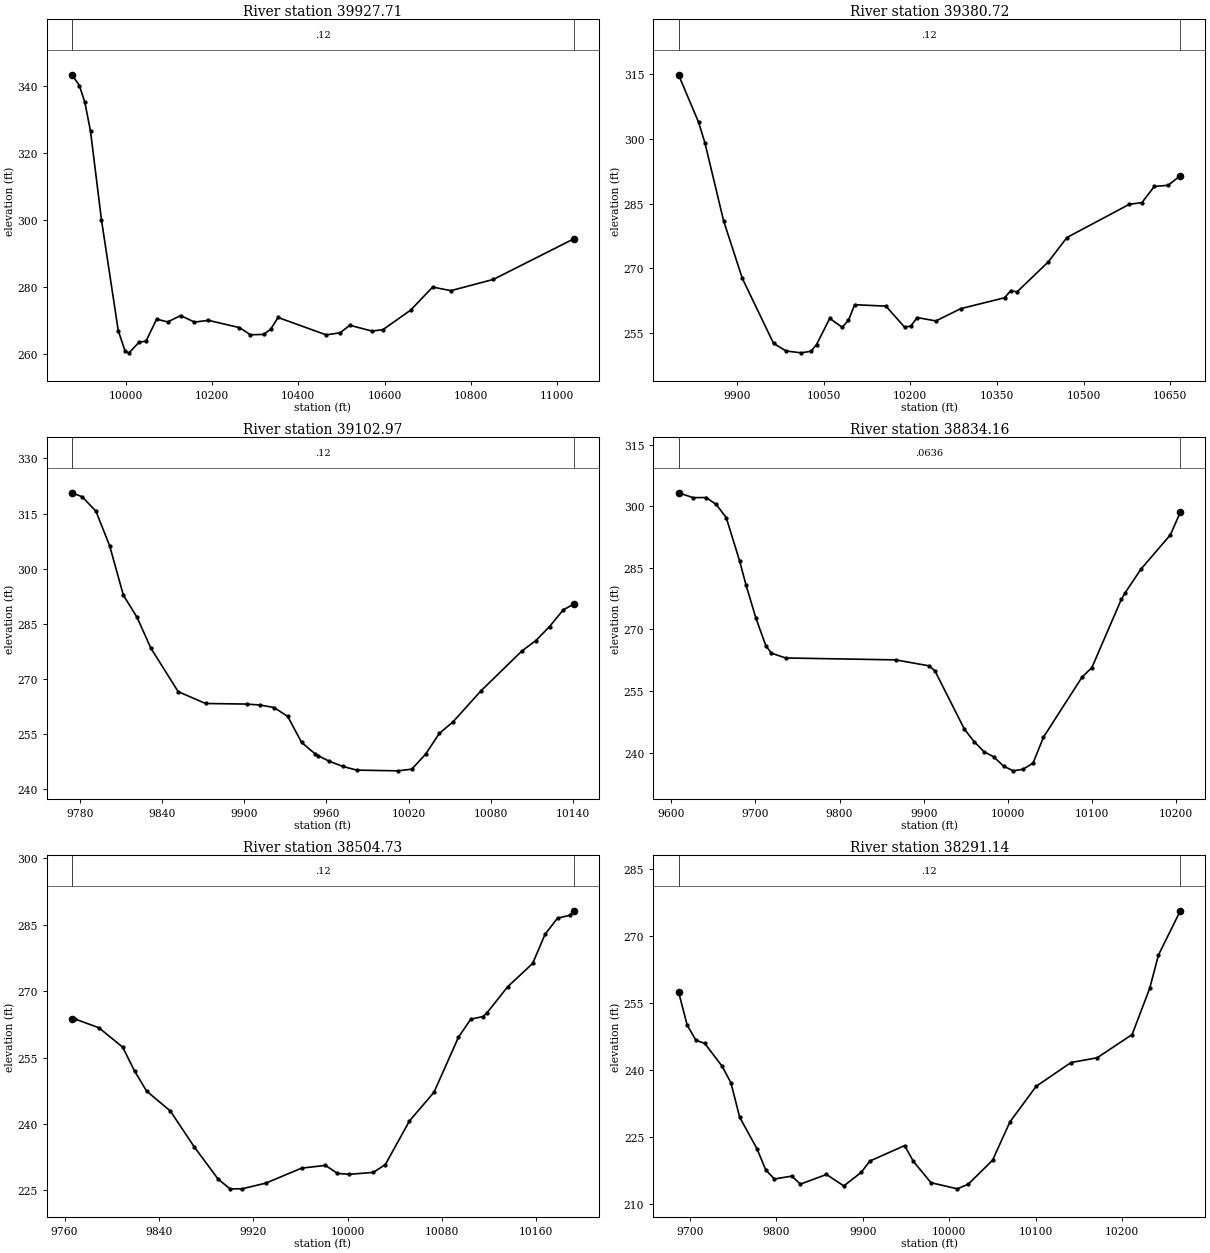
Type RM Length L Ch R = 1 ,39927.71,546.990100,546.990100,546.990100
XS GIS Cut Line= 2
865631.781182087840921.655948023866540.835406925840197.565845863
#Sta/Elev= 30
9876.159343.22729893.058340.01169905.843334.98999918.942326.35319944.197300.0482
9983.144266.98839999.194260.813110008.12260.390710031.29263.564410047.35263.8774
10072.04270.424710097.61269.6035 10127.6271.4929 10159.7269.5453 10191.8270.0754
10263.81267.910510289.38265.7657 10320.2265.879810336.25267.4557 10353.3 270.927
10464.65265.745410496.76266.3486 10519.5 268.59910570.64266.878610596.21267.2958
10660.13273.086810711.27279.982510753.56278.9122 10851.9282.262911038.35294.3564
#Mann= 3 , 0 , 0
9876.159    0.12       09876.159    0.12       011038.35    0.12       0
#XS Ineff= 2 , 0
       0                10586.95       0
Bank Sta=9876.159,11038.35
Exp/Cntr=0.3,0.1

Type RM Length L Ch R = 1 ,39380.72,277.754500,277.754500,277.754500
XS GIS Cut Line= 2
 866194.72857818841047.223132757866522.962430722840243.385563197
#Sta/Elev= 30
9798.985314.88879833.791 303.8259844.593 299.1049876.998280.96429909.402267.6056
 9963.41252.52569985.013250.753610011.33250.324810028.22250.700510037.78252.2385
10060.62258.328110082.23256.244810093.03257.897810103.83261.504410157.84261.1664
10190.24256.280510201.04256.557910211.85258.523510244.25257.729310287.46260.5917
10363.07263.110710373.87264.777110384.67264.469310438.68271.430610471.08277.1054
 10579.1284.8231 10600.7285.196110622.31  288.9610646.19289.230210667.26291.4495
#Mann= 3 , 0 , 0
9798.985    0.12       09798.985    0.12       010667.26    0.12       0
#XS Ineff= 2 , 0
       0                10277.78       0
Bank Sta=9798.985,10667.26
Exp/Cntr=0.3,0.1

Type RM Length L Ch R = 1 ,39102.97,268.810100,268.810100,268.810100
XS GIS Cut Line= 6
866537.521073801840992.428206467866537.088951922840831.808715657
866525.619873391840727.340739175866525.400618399840725.352792779
866516.991919013840642.986220149866516.273273265840627.273636207
#Sta/Elev= 30
9774.383320.64969781.812319.54639791.812315.63019801.812306.21269811.812292.7732
9821.812286.72919831.812278.39679851.812266.49759871.812263.26659901.812263.1076
9911.812262.84119921.812262.16649931.812259.72879941.853252.69059951.913249.4932
9954.145249.02219961.973 247.5549972.033246.12759982.093245.121710012.27244.9235
10022.33245.381810032.39249.450610042.45255.121610052.51258.297310072.61266.6308
10102.77277.588910112.82280.380910122.87284.216110132.89288.766510140.62290.3585
#Mann= 3 , 0 , 0
9774.383    0.12       09774.383    0.12       010140.62    0.12       0
#XS Ineff= 2 , 0
       0                               0
Bank Sta=9774.383,10140.62
Exp/Cntr=0.3,0.1

Type RM Length L Ch R = 1 ,38834.16,329.423800,329.423800,329.423800
XS GIS Cut Line= 6
866585.417957874841092.304458697866613.700826134841049.735173846
866679.684815047840943.504531203 866708.25409283840901.337220737
 866710.82962587840898.068829824866898.650718328840584.815202892
#Sta/Elev= 30
9608.644303.27849625.959302.08889641.425302.12189653.431 300.4359665.327297.2391
9681.167286.73769688.871280.80679700.643272.74389712.415266.03659719.072264.2135
9735.959263.04529866.801262.57719906.352261.1331 9913.44259.90839948.419245.7278
9960.079242.66229971.738240.23159983.398238.95679995.058236.695610006.72235.5549
10018.38235.954610030.04237.448110042.48243.757510088.34258.3895   10100260.6946
10134.97277.301610139.71278.961310158.29284.668610193.27293.015110205.15298.5442
#Mann= 3 , 0 , 0
9608.644  0.0636       09608.644  0.0636       010205.15  0.0636       0
#XS Ineff= 2 , 0
       0                               0
Bank Sta=9608.644,10205.15
Exp/Cntr=0.3,0.1

Type RM Length L Ch R = 1 ,38504.73,213.595600,213.595600,213.595600
XS GIS Cut Line= 6
866692.569196729841088.795006271866929.381000811841052.391446595
866931.341149429841051.994188922866973.540238467841043.322206819
867043.666695514841023.452942437867108.112078661841001.547837917
#Sta/Elev= 30
9766.364263.64349768.823 263.7099789.058261.74189809.293257.34849819.411251.9454
9829.528247.44129849.763242.90869869.998234.81689890.233227.5408 9900.35225.3348
9910.468225.33879930.703226.62369961.055230.0161 9981.29230.63529991.408228.8257
10001.53228.6137 10021.9229.055610032.11230.833310052.56240.687210073.34247.1475
10094.13 259.61310104.52263.664210114.92264.271510118.25265.0805 10135.9271.0158
10157.02276.256910167.58282.851710178.14286.5126 10188.7287.137610191.99288.1664
#Mann= 3 , 0 , 0
9766.364    0.12       09766.364    0.12       010191.99    0.12       0
#XS Ineff= 2 , 0
       09917.882                       0
Bank Sta=9766.364,10191.99
Exp/Cntr=0.3,0.1

Type RM Length L Ch R = 1 ,38291.14,244.637600,244.637600,244.637600
XS GIS Cut Line= 6
866635.195901299841297.685150453866720.956679558841284.432822894
866886.325032863 841270.34751488866986.354747988 841251.31008433
867140.606186497841230.984003289867209.949432679841218.866114788
#Sta/Elev= 30
9686.899257.5791 9696.88250.1229 9707.06246.71339717.241246.03189737.488240.8594
9747.565237.16319757.642229.4943 9777.78222.38119787.817 217.6789797.853215.6544
9817.925   216.39827.961214.5008 9858.07 216.6699878.143 214.0999898.215 217.131
9908.251219.66989948.512223.13749958.682219.58129979.022214.820910009.57213.4484
10022.34214.526310050.24219.858510070.41228.462710100.67236.408410141.02241.7419
10171.27242.806510211.71248.005710232.02 258.33510242.17265.8012 10267.5275.7325
#Mann= 3 , 0 , 0
9686.899    0.12       09686.899    0.12       0 10267.5    0.12       0
#XS Ineff= 2 , 0
       0                               0
Bank Sta=9686.899,10267.5
Exp/Cntr=0.3,0.1

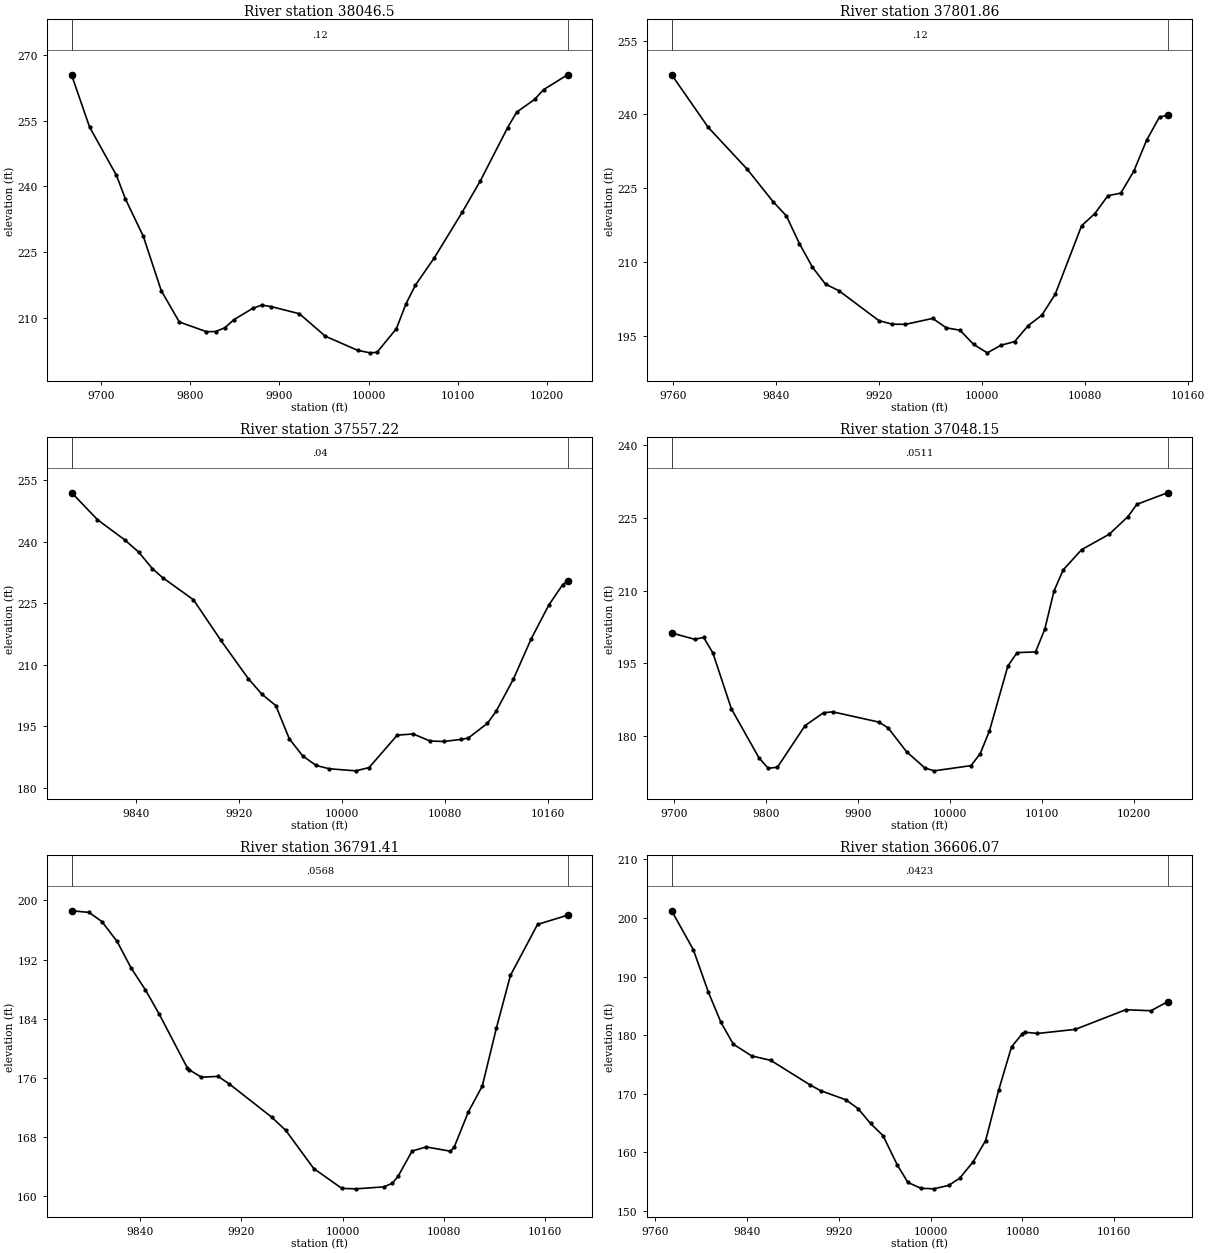
Type RM Length L Ch R = 1 , 38046.5,244.637700,244.637700,244.637700
XS GIS Cut Line= 6
866605.061107768841423.862464761 866766.11598244841438.010033949
866828.093027082841454.559589385867008.511777169841525.399972717
867089.409262076841540.558876204867141.890069547841541.887019007
#Sta/Elev= 30
 9667.64 265.317 9687.59253.53799717.649242.50969727.678237.13669747.735228.5972
9767.793 216.193 9788.02209.02679818.468206.80529828.617206.83279838.945 207.697
9849.295209.56299869.996212.10969880.347212.88819890.697212.54919922.536210.9026
9951.573205.77189987.588202.559410001.47 201.97610009.37202.086510031.08207.4883
10041.92213.213110052.47217.464410073.59223.690410104.74234.077110125.22241.3035
10155.71253.437410165.79256.945510185.85259.856510195.87262.085110222.79265.4808
#Mann= 3 , 0 , 0
 9667.64    0.12       0 9667.64    0.12       010222.79    0.12       0
#XS Ineff= 2 , 0
       0                               0
Bank Sta=9667.64,10222.79
Exp/Cntr=0.3,0.1

Type RM Length L Ch R = 1 ,37801.86,244.637700,244.637700,244.637700
XS GIS Cut Line= 6
866606.802612253 841669.70835412866724.613445227841686.077807506
866790.194214385 841703.38470406866888.419613666841737.998281253
866933.867554504841747.695533416866981.193831563841748.505441012
#Sta/Elev= 30
9759.019248.04149787.329237.38559817.576228.88219837.866222.24199848.011219.4087
9858.156213.77599868.302208.97659878.454205.52439888.797204.20979919.824198.1322
9930.166197.40749940.508197.37569961.588198.57559972.197196.66819982.806196.1807
9993.415193.294310004.01191.586710014.61193.123410025.21193.8706 10035.8197.1233
 10046.4199.239410056.76203.498110077.21217.381410087.43219.837710097.63223.4811
10107.65224.023110117.67 228.41310127.69234.759710137.72239.475510143.93239.8103
#Mann= 3 , 0 , 0
9759.019    0.12       09759.019    0.12       010143.93    0.12       0
#XS Ineff= 2 , 0
       0                               0
Bank Sta=9759.019,10143.93
Exp/Cntr=0.3,0.1

Type RM Length L Ch R = 1 ,37557.22,509.074400,509.074400,509.074400
XS GIS Cut Line= 6
866646.113723912842028.512349668866800.644269601841972.936322021
866869.956190111841955.652327804866887.354210221841947.127592945
866903.592642471 841934.34909703 866977.68348782841854.635502498
#Sta/Elev= 30
9790.464251.98459810.355245.43819831.647240.46789842.278 237.5459852.919233.5127
  9860.9231.29499884.843 225.8969906.125215.98299927.407206.65199938.048202.8195
9948.689200.0938 9959.19191.98089969.509187.83679979.828  185.519990.147184.6846
10010.73184.177610021.03184.967110042.89192.880710055.24193.175710068.26191.4635
10078.84191.334310092.38191.840810097.91192.167110112.73195.730210119.47198.6534
10133.02206.572310146.57 216.23310160.35224.555410171.23229.591310175.02230.5514
#Mann= 3 , 0 , 0
9790.464    0.04       09790.464    0.04       010175.02    0.04       0
#XS Ineff= 2 , 0
       0                               0
Bank Sta=9790.464,10175.02
Exp/Cntr=0.3,0.1

Type RM Length L Ch R = 1 ,37048.15,256.737900,256.737900,256.737900
XS GIS Cut Line= 2
866960.251714438842150.241450014867498.157358856842118.850025567
#Sta/Elev= 30
9697.533 201.2559722.323199.9659 9732.34200.32839742.357197.10089762.391185.5889
9792.442175.44039802.459173.30119812.476173.52819842.527182.13449862.561184.7787
9872.578184.96279922.664182.84669932.681181.65789952.715176.73099972.749173.3598
9982.766172.774510022.83173.853610032.85176.339410042.87181.0509 10062.9 194.469
10072.92197.201710092.95 197.34510102.97 202.03610112.99209.9361   10123214.2936
10143.04218.479910173.09221.670710193.12225.258310203.14 227.84710236.35230.2239
#Mann= 3 , 0 , 0
9697.533  0.0511       09697.533  0.0511       010236.35  0.0511       0
#XS Ineff= 2 , 0
       0                               0
Bank Sta=9697.533,10236.35
Exp/Cntr=0.3,0.1

Type RM Length L Ch R = 1 ,36791.41,185.344100,185.344100,185.344100
XS GIS Cut Line= 2
866932.706185502842254.603282933867285.726708239842425.358574293
#Sta/Elev= 30
9785.819198.59549799.475198.37539809.695197.13169821.692194.4455  9832.8190.8445
9843.909187.95219855.017184.61849877.234177.35519878.592177.11519888.342176.1031
9901.558176.21499910.559175.17349943.884170.71339954.993168.93299977.209163.7579
9999.426161.078110010.53161.017410032.75161.284210039.35161.775710043.86162.7088
10054.97166.121510066.08  166.6810085.28166.103110088.29166.6583 10099.4171.3906
10110.51174.916310121.62182.728710132.73189.849310154.18196.748310177.97197.9999
#Mann= 3 , 0 , 0
9785.819  0.0568       09785.819  0.0568       010177.97  0.0568       0
#XS Ineff= 2 , 0
       0                               0
Bank Sta=9785.819,10177.97
Exp/Cntr=0.3,0.1

Type RM Length L Ch R = 1 ,36606.07,339.066700,339.066700,339.066700
XS GIS Cut Line= 6
866845.589706601842427.583352186 867036.94753681 842509.41461382
867069.479906115842526.523555516867071.231521077842527.488877721
867134.703653611842561.010015267867238.138490776842608.299916906
#Sta/Elev= 30
 9774.17201.23749793.033194.59769806.157187.36049817.033182.23389827.909178.4745
9843.899176.46619860.537175.71329894.765171.53029904.041170.53939925.793169.0037
9936.669167.49539947.545164.93649958.421162.87659971.063157.80739980.173154.8753
9991.389153.889510002.69153.785710015.77154.381510025.31155.600210037.13158.4224
10047.93162.019510059.24170.577310070.55178.034610079.96180.248610081.85180.5243
10093.15180.295710126.14181.000810170.12184.349310192.11184.183310206.56185.7006
#Mann= 3 , 0 , 0
 9774.17  0.0423       0 9774.17  0.0423       010206.56  0.0423       0
#XS Ineff= 2 , 0
       0                               0
Bank Sta=9774.17,10206.56
Exp/Cntr=0.3,0.1