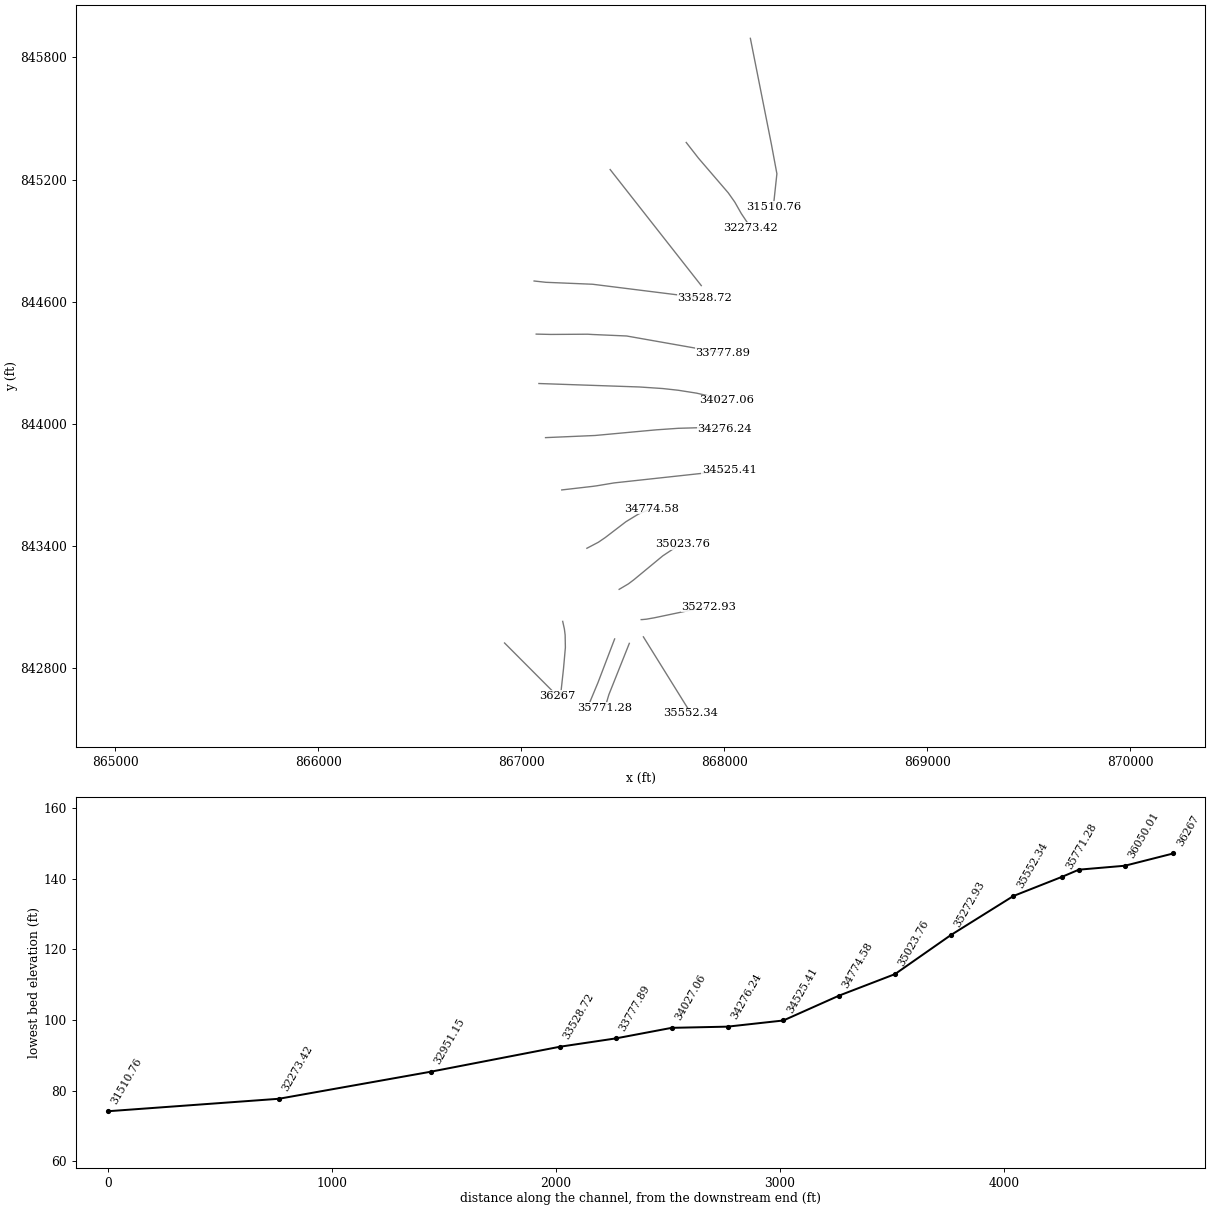
HEC-RAS study 16857_ras.prj: 16857

--- 16857_ras.g01 (geometry) --- (continued)

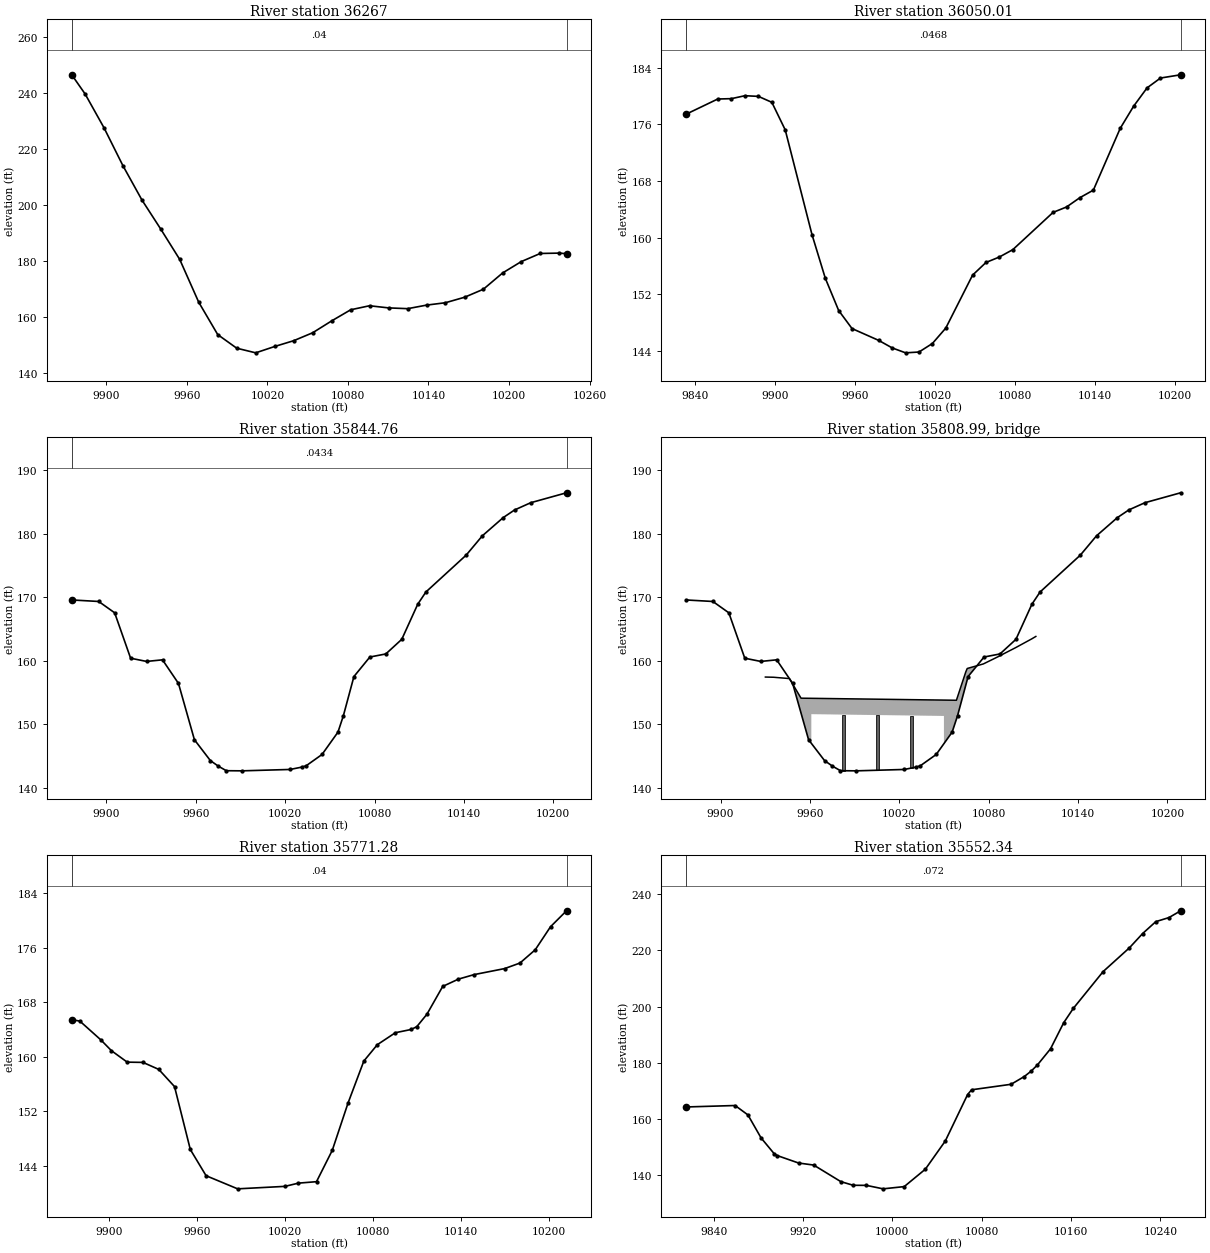
Type RM Length L Ch R = 1 ,   36267,216.991100,216.991100,216.991100
XS GIS Cut Line= 2
866918.127825672842922.027738783 867178.61972732842661.147626143
#Sta/Elev= 28
9874.174246.41299884.105239.60669898.237227.50349912.368213.9527  9926.5201.7476
 9940.51191.38039954.663 180.5479968.816165.28819982.968153.74489997.121148.8938
10011.27  147.2410025.42149.508710039.58151.572210053.68154.393810067.88158.6395
10082.04162.597910096.08164.032410110.21163.2726 10124.5162.994810138.65164.2667
10152.61  165.1110166.95167.076510180.87169.916710195.26175.735910209.13179.7801
10223.26182.6791 10237.4182.808210242.84182.6053
#Mann= 3 , 0 , 0
9874.174    0.04       09874.174    0.04       010242.84    0.04       0
#XS Ineff= 2 , 0
       0                               0
Bank Sta=9874.174,10242.84
Exp/Cntr=0.3,0.1

Type RM Length L Ch R = 1 ,36050.01,205.249500,205.249500,205.249500
XS GIS Cut Line= 6
867204.399228987843028.288008657867212.708836983842990.642006481
 867216.41065501842961.282958797867217.566390124842899.604086378
867208.355830905842795.861925723867193.459422225842659.968087243
#Sta/Elev= 30
9833.384 177.4219857.232179.57799867.473179.63069877.622180.04549887.702179.9526
9897.781179.1147 9907.82 175.2189927.851160.44589937.855154.26629947.856149.7169
9957.857147.1692 9977.91145.49429987.947144.43819997.994143.742110008.03143.8571
10018.07145.058810028.11147.236810048.19154.715310058.23156.501310068.27157.2733
10078.33158.310710108.51163.573410118.57164.333810128.63165.654710138.69166.7149
10158.81175.437210168.87178.568110178.93181.153110188.99182.541810204.11183.0015
#Mann= 3 , 0 , 0
9833.384  0.0468       09833.384  0.0468       010204.11  0.0468       0
#XS Ineff= 2 , 0
       0                               0
Bank Sta=9833.384,10204.11
Exp/Cntr=0.3,0.1

Type RM Length L Ch R = 1 ,35844.76,73.482600,73.482600,73.482600
XS GIS Cut Line= 3
867460.107345629842941.919012644867377.973213391842727.074756036
867338.628676262842632.877068023
#Sta/Elev= 30
9876.762169.56369894.875 169.3239905.581167.53649916.287160.37879926.993159.8724
9937.698160.12389948.404156.4096 9959.11147.53139969.816144.24519975.077143.3758
9980.522142.64729991.228142.627110023.35142.844710031.08143.209210034.05143.4165
10044.76145.204110055.46148.728510059.09151.312410066.17157.489210076.87160.5677
10087.58161.051110098.29163.358310109.02168.897610114.49170.819210141.53176.6334
10152.37179.673510166.38182.545510174.04183.752210184.88184.892510208.85186.4559
#Mann= 3 , 0 , 0
9876.762  0.0434       09876.762  0.0434       010208.85  0.0434       0
#XS Ineff= 2 , 0
       09954.205         10056.7       0
Bank Sta=9876.762,10208.85
Exp/Cntr=0.3,0.1

Type RM Length L Ch R = 3 ,35808.99,,,
BEGIN DESCRIPTION:
END DESCRIPTION:
Bridge Culvert--1,0,-1,-1, 0
Deck Dist Width WeirC Skew NumUp NumDn MinLoCord MaxHiCord MaxSubmerge Is_Ogee
24.241300,25.000000,2.6,0, 18, 18, , , 0.95, 0, 0,0,,
 9930.11 9935.41 9935.53 9946.26 9954.05 9960.95 9960.9510049.9510049.9510058.32
10064.6010065.5810076.4310087.2710090.4110098.1210108.9710111.64
  157.41  157.38  157.38  157.17  154.08  154.06  154.06  153.78  153.78  153.75
  158.21  158.76  159.48  160.73  161.12  162.05  163.44  163.81
 -842.59 -842.62 -842.62 -842.83 -845.92 -845.94  151.56  151.28 -846.22 -846.25
 -841.79 -841.24 -840.52 -839.27 -838.88 -837.95 -836.56 -836.19
 9930.11 9935.41 9935.53 9946.26 9954.05 9962.50 9962.5010051.5010051.5010058.32
10064.6010065.5810076.4310087.2710090.4110098.1210108.9710111.64
  157.41  157.38  157.38  157.17  154.08  154.05  154.05  153.77  153.77  153.75
  158.21  158.76  159.48  160.73  161.12  162.05  163.44  163.81
 -842.59 -842.62 -842.62 -842.83 -845.92 -845.95  151.55  151.27 -846.23 -846.25
 -841.79 -841.24 -840.52 -839.27 -838.88 -837.95 -836.56 -836.19
Pier Skew, UpSta & Num, DnSta & Num=  ,9982.70, 2 ,9984.25, 2 , 0 , 0 , 0 ,,
    2.00    2.00
 -846.01  153.99
    2.00    2.00
 -846.02  153.98
Pier Skew, UpSta & Num, DnSta & Num=  ,10005.45, 2 ,10007.00, 2 , 0 , 0 , 0 ,,
    2.00    2.00
 -846.08  153.92
    2.00    2.00
 -846.09  153.91
Pier Skew, UpSta & Num, DnSta & Num=  ,10028.20, 2 ,10029.75, 2 , 0 , 0 , 0 ,,
    2.00    2.00
 -846.16  153.84
    2.00    2.00
 -846.16  153.84
BR Coef=-1 , 0 , 0 ,, 0 ,,,0.8,0,1,0,
WSPro=,,,, 1 ,,,, 0 ,,,, 0 ,,,,-1 ,-1 ,-1 , 0 , 0 , 0 , 0 , 0
BC Design=,, 0 ,, 0 ,,,,,,

Type RM Length L Ch R = 1 ,35771.28,218.941400,218.941400,218.941400
XS GIS Cut Line= 3
867532.413607078842920.174032648867431.709798038842668.170285061
867412.799830935842604.534675377
#Sta/Elev= 30
9874.348165.4816 9879.92165.26369894.327162.49019901.458160.92439912.227159.2413
9922.996159.20519933.765158.17859944.533155.65129955.302146.42059966.071142.5701
9987.609140.642910019.92141.005910029.07141.479110041.45141.694910052.22146.2987
10062.99153.244710073.76159.402110082.97161.8048 10095.3163.563410106.07164.0382
10109.91164.451210116.84 166.278 10127.6170.358510138.37171.432310149.04172.0931
 10169.9172.977710180.33173.790610190.76175.7344 10201.2179.119910212.11181.4629
#Mann= 3 , 0 , 0
9874.348    0.04       09874.348    0.04       010212.11    0.04       0
#XS Ineff= 2 , 0
       0 9954.03        10059.98       0
Bank Sta=9874.348,10212.11
Exp/Cntr=0.3,0.1

Type RM Length L Ch R = 1 ,35552.34,279.405100,279.405100,279.405100
XS GIS Cut Line= 2
867601.706675309842952.154056001867835.798438664842576.086203761
#Sta/Elev= 30
9815.172164.2908 9859.25164.80779870.715161.45939882.494153.26979894.273147.6254
9897.096146.97249916.019144.34679929.611143.61069953.866137.72579964.948136.4172
9976.727136.38949991.712135.152310010.63135.946310029.56142.1469 10047.4152.1698
 10067.4168.721410070.96170.4035 10106.3172.361510118.08 175.10710124.17177.0041
10129.86179.230710141.63184.985410153.41194.266610162.02199.371610188.75212.4877
10212.31220.953410224.09226.016310235.87230.249410247.65231.696410258.15234.1174
#Mann= 3 , 0 , 0
9815.172   0.072       09815.172   0.072       010258.15   0.072       0
#XS Ineff= 2 , 0
       0                               0
Bank Sta=9815.172,10258.15
Exp/Cntr=0.3,0.1

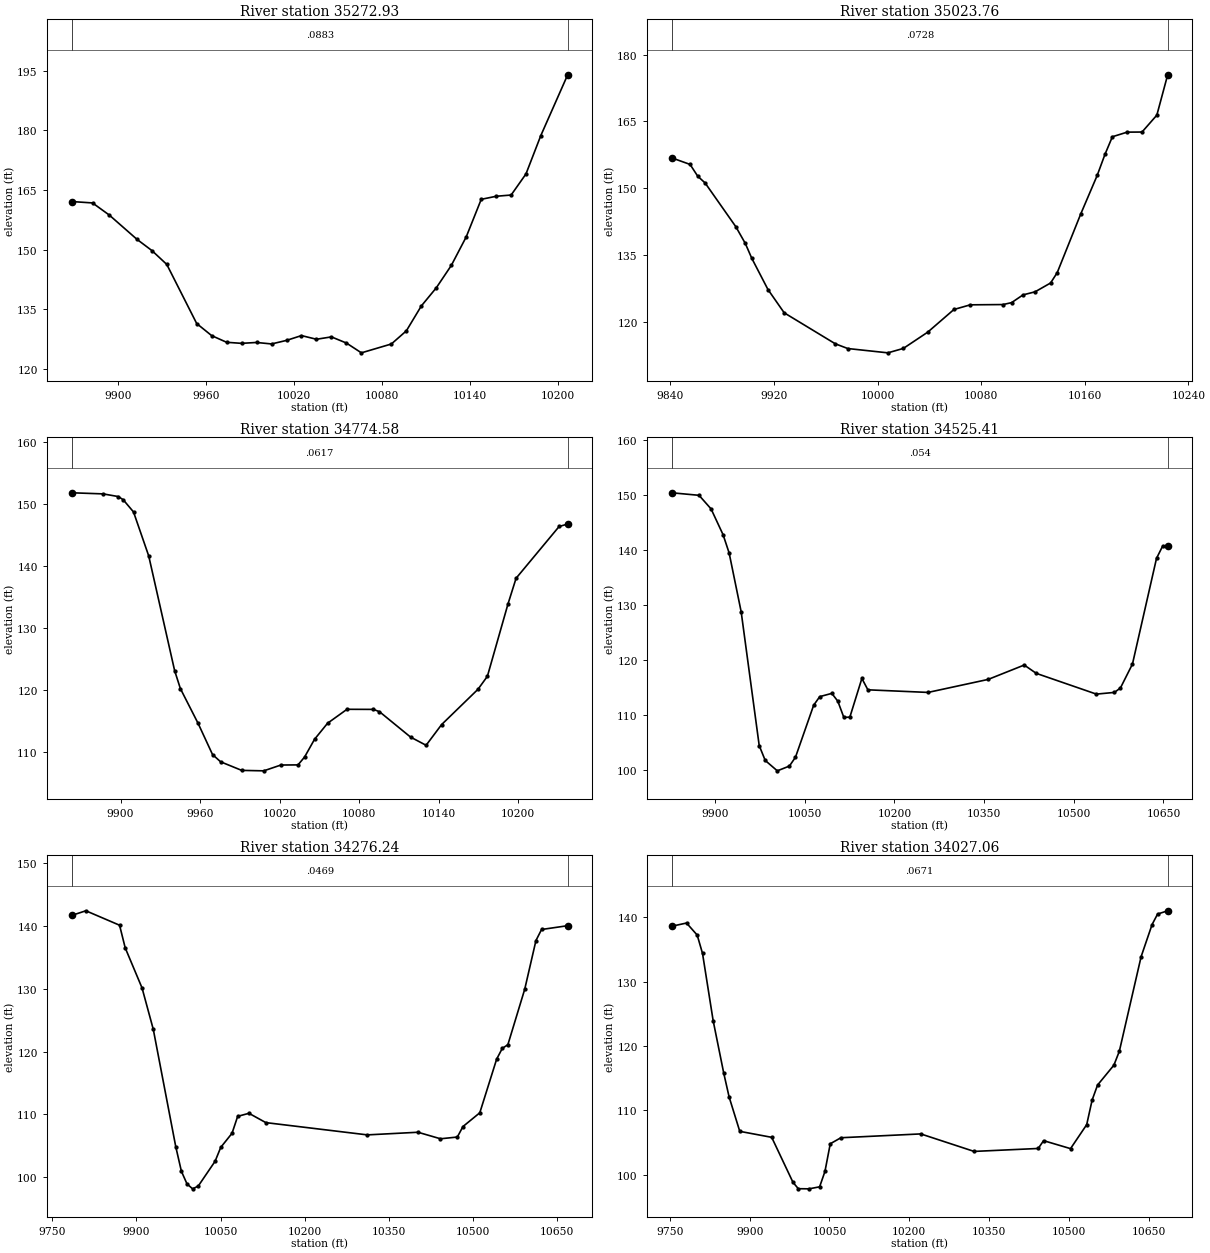
Type RM Length L Ch R = 1 ,35272.93,249.173300,249.173300,249.173300
XS GIS Cut Line= 6
867590.877881508 843037.05205873867594.425450633843037.003221152
867616.399639828843039.055795413 867655.63662825843045.952960161
867880.082939732843092.902681132867923.083238501843099.866068722
#Sta/Elev= 30
9868.277162.08929882.445161.73979893.894158.6839 9912.78 152.5869922.933149.7719
9933.087146.29279953.504131.42989963.715128.39139973.925126.71729984.136126.4513
9994.347126.672910004.56 126.29910014.77127.192910024.99128.401110035.21127.4789
10045.43128.074510055.65126.525310065.87124.065610086.31126.290510096.53129.5892
10106.75135.847610116.97140.412310127.19146.025710137.41153.232210147.62 162.645
10157.84163.416510168.02163.728510178.15169.032810188.28 178.683 10206.6 193.949
#Mann= 3 , 0 , 0
9868.277  0.0883       09868.277  0.0883       0 10206.6  0.0883       0
#XS Ineff= 2 , 0
       0                               0
Bank Sta=9868.277,10206.6
Exp/Cntr=0.3,0.1

Type RM Length L Ch R = 1 ,35023.76,249.173200,249.173200,249.173200
XS GIS Cut Line= 6
867482.404906469  843185.7560164867527.876756613 843212.65944195
867554.527993933843232.649940248 867697.24798372843350.392077391
867749.998500609843385.393718618867792.316905741843408.971064318
#Sta/Elev= 30
9841.006156.80669855.127155.33689861.075152.68119866.759  151.179890.486141.3388
9897.799137.58719902.803134.24519915.303127.22969927.835     1229967.333115.0342
9976.946113.973310007.91113.005710019.85113.997110038.66117.643710058.94122.7452
10071.57123.791810096.83123.852610103.46124.283910112.29126.0235 10121.6126.7138
 10133.6128.699810138.71131.0199 10156.8144.1431 10169.6152.8676 10175.6157.5985
10181.32161.553210192.77  162.5910204.22162.613210215.67166.408110224.04175.4754
#Mann= 3 , 0 , 0
9841.006  0.0728       09841.006  0.0728       010224.04  0.0728       0
#XS Ineff= 2 , 0
       0                               0
Bank Sta=9841.006,10224.04
Exp/Cntr=0.3,0.1

Type RM Length L Ch R = 1 ,34774.58,249.173300,249.173300,249.173300
XS GIS Cut Line= 6
867323.561518435843387.637073854867380.238696045843417.371717155
867414.380824406843440.672796245867515.995206879 843518.34896919
867578.447620538 843556.33294984867640.955833658843582.270926554
#Sta/Elev= 30
9863.163151.80869886.798151.6294 9898.27151.19789901.983150.68159909.743148.7138
9921.215141.61349940.758123.10069945.097120.19799958.497114.57199969.356109.5514
9975.451108.38039991.376 106.99310008.01106.919410020.93107.857510033.85 107.879
10038.82109.154510046.31112.009410056.13114.599910070.81116.855110090.74116.8379
10095.32116.466510118.78112.365510130.49111.045210142.19114.387610169.63120.0847
10176.73122.182910192.25133.845110198.38138.009710230.86146.368510237.31146.7594
#Mann= 3 , 0 , 0
9863.163  0.0617       09863.163  0.0617       010237.31  0.0617       0
#XS Ineff= 2 , 0
       0                               0
Bank Sta=9863.163,10237.31
Exp/Cntr=0.3,0.1

Type RM Length L Ch R = 1 ,34525.41,249.173300,249.173300,249.173300
XS GIS Cut Line= 6
867199.691702436843674.372762248867352.907380706843692.020618358
867369.936848559843694.343534941867371.917487039843694.621152002
 867457.59275551843708.919757185868023.580386907843770.329105634
#Sta/Elev= 30
9827.584150.40149873.192149.93979893.324147.46919913.456142.76669923.523139.4663
9943.655128.77659973.853104.44499983.925101.745410004.1399.85601 10024.4100.7256
10034.54102.337910064.96111.788410075.09113.344810095.31113.937410105.37112.5111
10115.43109.565810125.49109.6215 10145.6116.650710155.66114.583310256.25114.1103
10356.84116.474410417.19119.088710437.31117.577610537.89113.802810568.07114.1131
10578.13114.919610598.25119.271510638.48138.480710648.54140.670810657.17140.8066
#Mann= 3 , 0 , 0
9827.584   0.054       09827.584   0.054       010657.17   0.054       0
#XS Ineff= 2 , 0
       0                 10225.2       0
Bank Sta=9827.584,10657.17
Exp/Cntr=0.3,0.1

Type RM Length L Ch R = 1 ,34276.24,249.173200,249.173200,249.173200
XS GIS Cut Line= 6
867119.919509485843931.462008192867363.327433851843941.962155729
867664.254318201843969.734671887867773.184158941843977.281946451
 867865.34968473 843979.94026131868001.453077714843975.143383703
#Sta/Elev= 30
9785.038141.71629810.129142.45289870.192140.14999880.202136.54729910.234130.1443
9930.255123.54149970.297104.82559980.307100.91449990.31898.8972210000.3398.11117
10010.3498.55306 10040.4102.514310050.44104.726910070.53106.970510080.57109.6707
10100.66110.155610130.78108.671610311.55106.7151 10401.8107.135110441.89106.0936
 10471.9106.371510481.91108.043410511.92110.239710541.93118.792210551.94120.5056
10561.94121.099910591.95129.940810611.96137.709510621.96139.467810668.49140.0749
#Mann= 3 , 0 , 0
9785.038  0.0469       09785.038  0.0469       010668.49  0.0469       0
#XS Ineff= 2 , 0
       0                10350.61       0
Bank Sta=9785.038,10668.49
Exp/Cntr=0.3,0.1

Type RM Length L Ch R = 1 ,34027.06,249.173300,249.173300,249.173300
XS GIS Cut Line= 6
867087.238747726844197.435830564867582.226183445844180.447246914
867696.989549308844172.735961114867772.734502956844164.398412013
867863.817568615844150.079818366868013.311910246844115.628372779
#Sta/Elev= 30
9753.568138.5915 9781.34139.09099801.348137.21739811.352134.36889831.359123.9082
9851.367115.71199861.371112.04739881.379106.70979941.402105.77859981.43298.77966
 9991.4497.7928110011.4697.7718210031.4798.0837210041.48100.472810051.49104.7805
 10071.5105.714710221.61106.309610321.79103.589610442.37104.047310452.49105.2606
10503.11104.022110533.49107.747310543.72111.576610553.94113.908810584.63116.9964
10594.86119.158310635.77 133.85410656.39138.852210666.76140.486610685.74140.9948
#Mann= 3 , 0 , 0
9753.568  0.0671       09753.568  0.0671       010685.74  0.0671       0
#XS Ineff= 2 , 0
       0                 10426.4       0
Bank Sta=9753.568,10685.74
Exp/Cntr=0.3,0.1

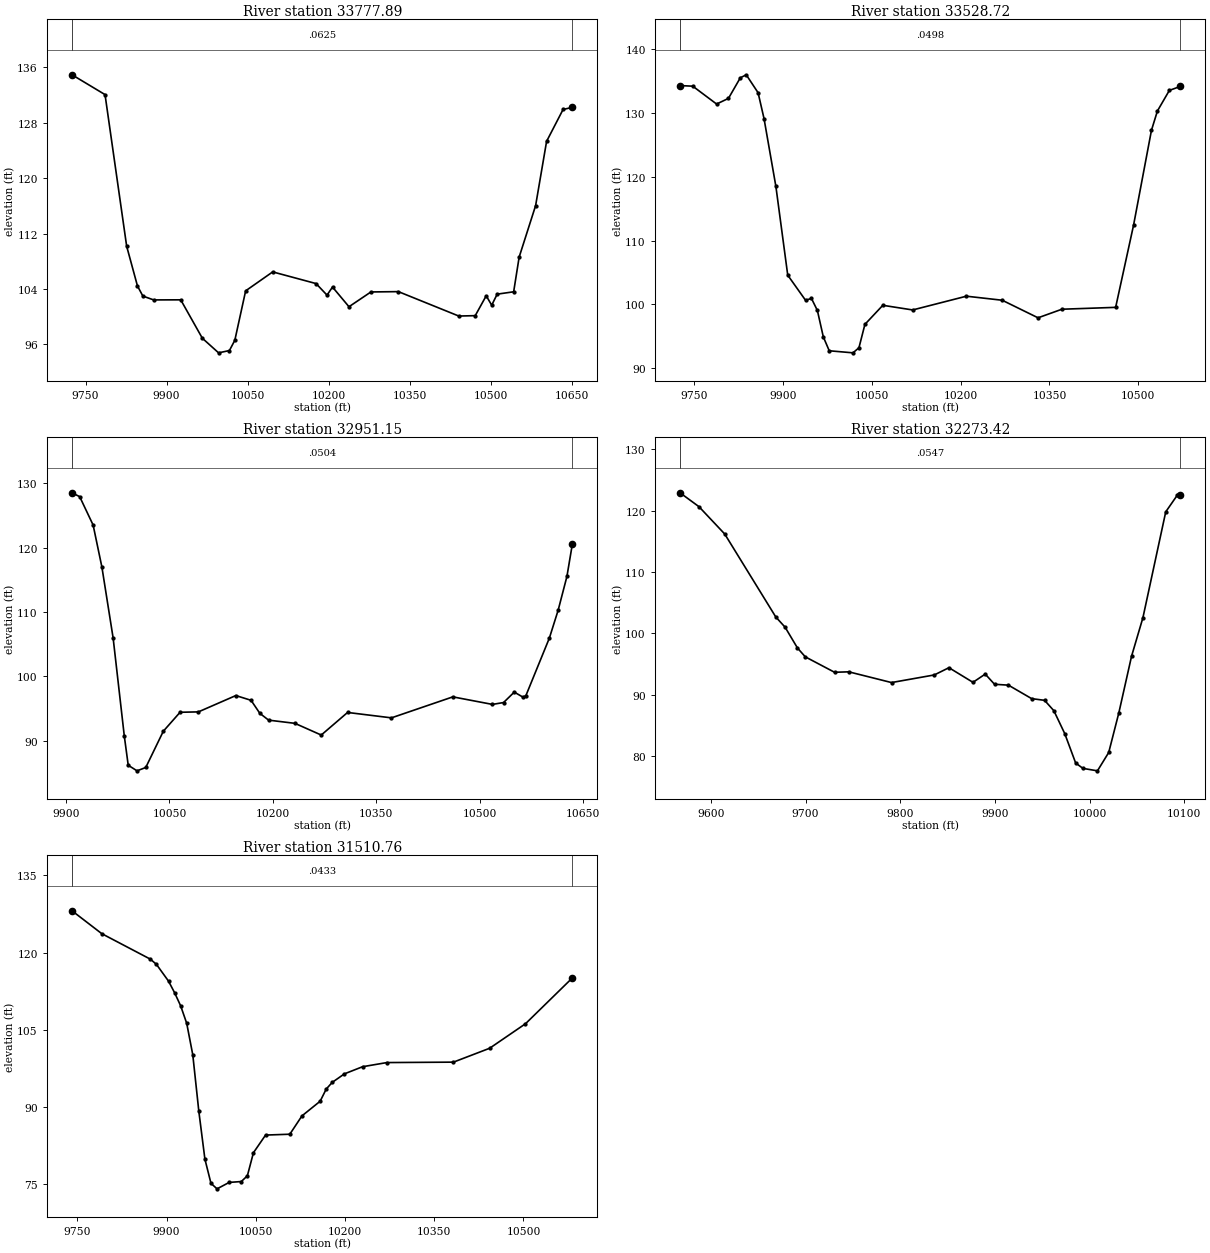
Type RM Length L Ch R = 1 ,33777.89,249.173300,249.173300,249.173300
XS GIS Cut Line= 6
867073.905437062844440.306284557867146.400054718844438.710933815
867327.091093063844439.788107857 867349.84243891844438.460414935
 867518.93642406844431.093242238867991.983050843844347.772192988
#Sta/Elev= 30
9725.002134.93999786.112132.07529826.115110.17799846.115104.43079856.115102.9767
9876.116102.42339926.117102.43729966.11796.888949996.14594.7800910016.1795.11015
10026.1896.59163 10046.2103.733810096.25106.470810176.41104.784910196.72103.1152
10206.87104.282510237.33101.439310277.95103.574110328.72103.621110440.41100.0958
10470.88  100.1510491.18103.019510501.34101.662110511.49103.256210541.95 103.597
10552.11108.607710582.57116.045210602.88125.327110633.34129.926810650.58130.2399
#Mann= 3 , 0 , 0
9725.002  0.0625       09725.002  0.0625       010650.58  0.0625       0
#XS Ineff= 2 , 0
       0                10488.56       0
Bank Sta=9725.002,10650.58
Exp/Cntr=0.3,0.1

Type RM Length L Ch R = 1 ,33528.72,577.570000,577.570000,577.570000
XS GIS Cut Line= 6
867063.597309218844701.366753674 867121.56393894844694.934526091
867335.635462976844686.021756469867337.634517489844685.960266116
867351.825126571844685.344849427867903.475773609844616.506331959
#Sta/Elev= 30
9726.421134.26129747.955134.16489788.182131.36989808.199 132.2559828.217135.4769
9838.225  135.959858.243133.13889868.251129.09339888.269118.47519908.286104.5762
9938.312100.65579948.321100.93399958.32999.051999968.33894.918829978.34792.74497
 10018.492.4214710028.4893.2146210038.5696.8790810068.7999.8635210119.18 99.1347
10209.88101.288610270.34100.655710330.8197.9060110371.1299.2485510461.8299.54132
10492.05112.398110522.28127.259410532.36 130.28910552.51133.506410571.13134.1305
#Mann= 3 , 0 , 0
9726.421  0.0498       09726.421  0.0498       010571.13  0.0498       0
#XS Ineff= 2 , 0
       0                               0
Bank Sta=9726.421,10571.13
Exp/Cntr=0.3,0.1

Type RM Length L Ch R = 1 ,32951.15,677.724100,677.724100,677.724100
XS GIS Cut Line= 2
867438.111832705845249.078472516867886.716895335844678.766760276
#Sta/Elev= 30
9908.638128.5418 9919.78127.93819939.273123.52619951.996116.99589968.304105.9569
9984.47890.736389990.16586.1973810002.8985.3252710015.6185.8472810041.0691.48195
10065.3594.4281410091.9594.4889110146.2397.0264410168.2996.2865710181.0194.26472
10193.7393.20569 10231.992.7067910270.0790.8883310308.2494.3991910371.8593.56006
10460.9196.8221610518.2495.6512510534.4295.9387510549.97 97.5632 10562.7 96.7708
10566.7797.0010310600.87105.959510613.59 110.28610626.31115.531810634.24 120.596
#Mann= 3 , 0 , 0
9908.638  0.0504       09908.638  0.0504       010634.24  0.0504       0
#XS Ineff= 2 , 0
       0                               0
Bank Sta=9908.638,10634.24
Exp/Cntr=0.3,0.1

Type RM Length L Ch R = 1 ,32273.42,762.666300,762.666300,762.666300
XS GIS Cut Line= 6
867812.667799602845382.219386761  867872.9229814845305.042849387
868019.531306603 845134.71280724868051.913515515845088.948856572
868084.023309341845032.495681647868131.239177362844962.152975338
#Sta/Elev= 30
9567.384122.88939587.423120.62699614.604116.18259668.533102.68499678.392101.0149
9691.43197.637269699.69996.199489730.57793.691349745.62193.763189790.75392.01757
9835.88693.254849851.39394.435059876.76292.054759889.697  93.3959899.53691.73858
9914.21791.594459938.71789.404039952.37589.126079962.176 87.43839973.67983.71176
9985.182 78.93519992.84278.05783 10008.277.65684 10020.180.6403810030.7787.07338
10044.1996.2818510056.24102.579110080.32119.785710092.37122.4629 10095.8122.5165
#Mann= 3 , 0 , 0
9567.384  0.0547       09567.384  0.0547       0 10095.8  0.0547       0
#XS Ineff= 2 , 0
       09853.095                       0
Bank Sta=9567.384,10095.8
Exp/Cntr=0.3,0.1

Type RM Length L Ch R = 1 ,31510.76,198.397500,198.397500,198.397500
XS GIS Cut Line= 4
868128.457781941845894.127386451868232.279142022845372.051528722
868259.072005689845228.450995997868241.638556629845066.630972847
#Sta/Elev= 30
9741.044128.12199791.134123.6737  9872.7118.73049882.896117.72629903.288114.4619
9913.483112.21319923.679109.66749933.875106.26379944.071 100.1579954.26789.15524
9964.46379.890069974.65875.191319984.85474.1228510005.2575.3709610025.6475.54026
10035.83 76.656910046.0381.1365810066.4284.56387 10107.284.73013 10127.688.29081
10158.1891.1364210168.3893.4997610178.5794.8062410198.9796.4517110229.5597.84002
10270.3498.6438810382.24 98.728110443.01101.418210503.36106.183710582.18 115.088
#Mann= 3 , 0 , 0
9741.044  0.0433       09741.044  0.0433       010582.18  0.0433       0
#XS Ineff= 2 , 0
       0                 10228.9       0
Bank Sta=9741.044,10582.18
Exp/Cntr=0.3,0.1