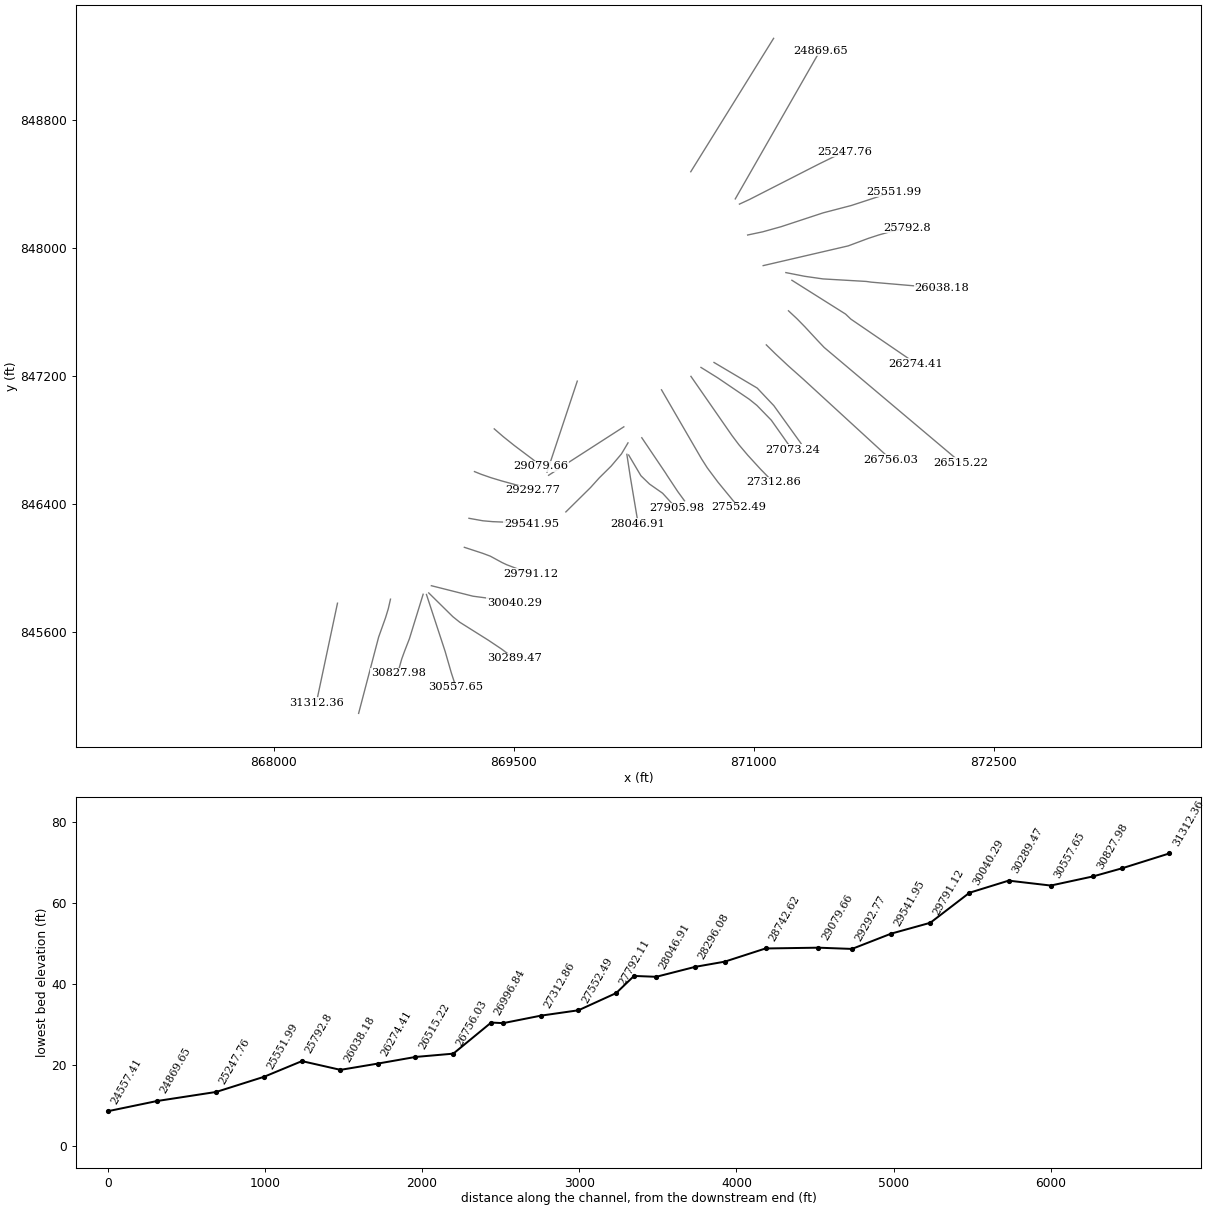
HEC-RAS study 16857_ras.prj: 16857

--- 16857_ras.g01 (geometry) --- (continued)

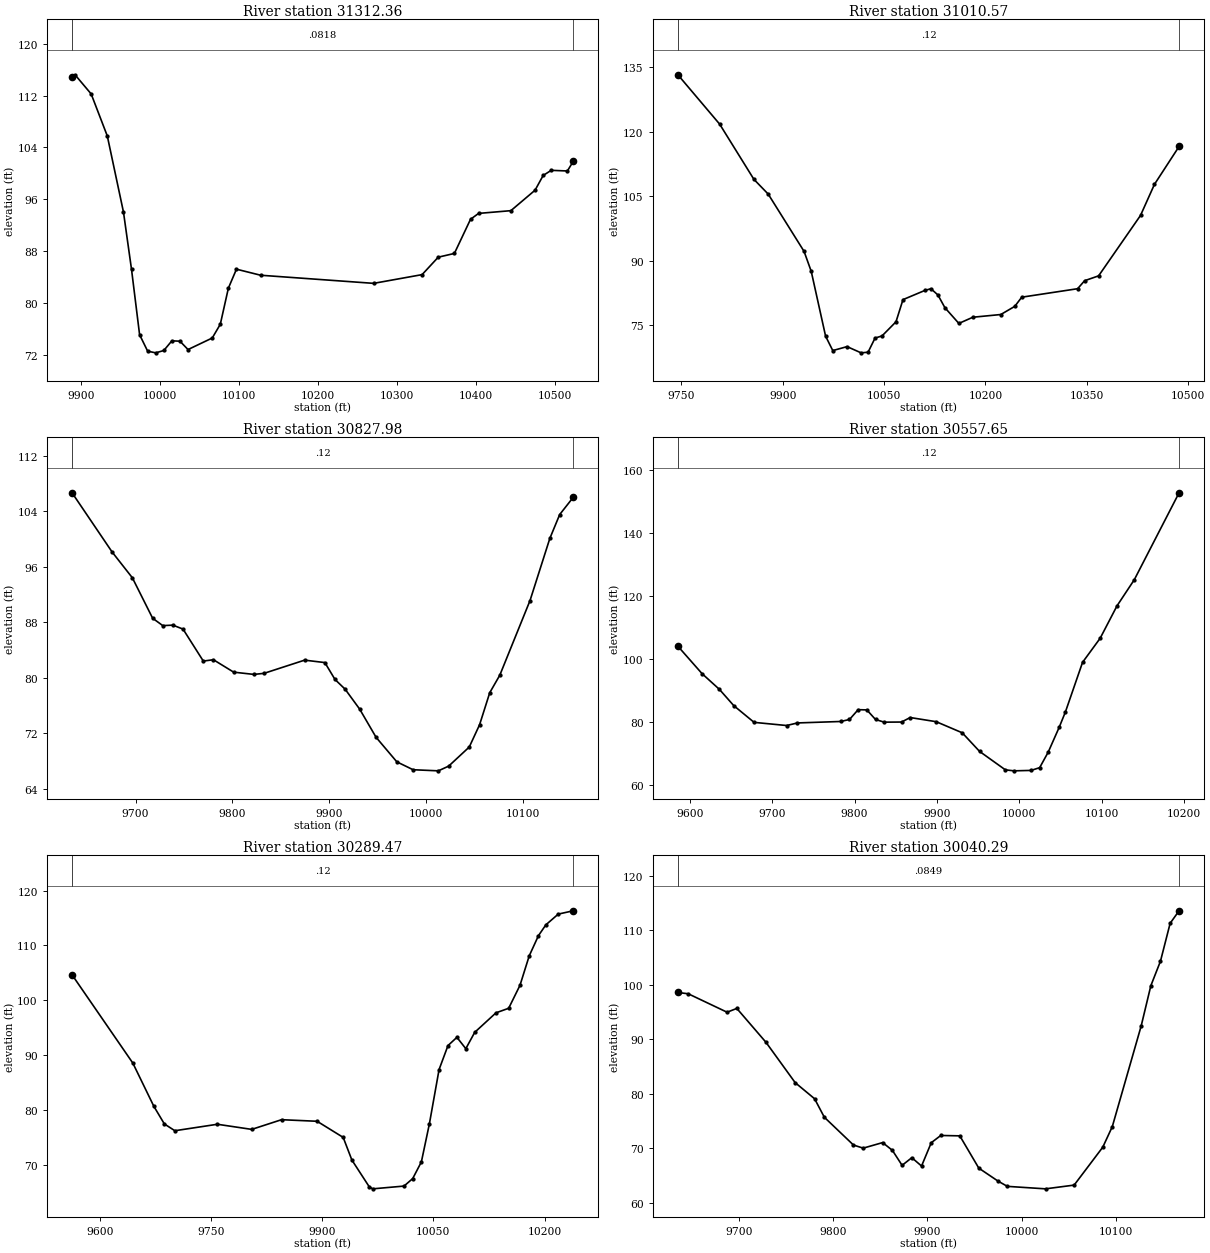
Type RM Length L Ch R = 1 ,31312.36,301.790300,301.790300,301.790300
XS GIS Cut Line= 2
868397.522302651845778.700427837868265.669037067845157.716013496
#Sta/Elev= 30
9888.725114.90149892.508115.20959912.954112.2499  9933.4105.75599953.84694.02686
9964.06985.155529974.29275.074569984.51572.533079994.73872.2795810004.96 72.6408
10015.1874.1349510025.4174.0764810035.6372.78722 10066.374.5695810076.5276.69486
10086.7482.2659710096.9785.1944910127.6484.2595410270.7683.0072510332.0984.35473
10352.5487.0477210372.99  87.62610393.4392.8970110403.6593.8074110444.55 94.2296
10475.2297.3949110485.4499.6664810495.66100.457610516.11100.357710523.55101.8462
#Mann= 3 , 0 , 0
9888.725  0.0818       09888.725  0.0818       010523.55  0.0818       0
#XS Ineff= 2 , 0
       0                10268.24       0
Bank Sta=9888.725,10523.55
Exp/Cntr=0.3,0.1

Type RM Length L Ch R = 1 ,31010.57,182.588600,182.588600,182.588600
XS GIS Cut Line= 6
868728.861768138845803.741645859868715.119197698845743.840999331
868697.877603969845687.598318971868655.244215243845568.094599665
868654.586226415845566.205935808868529.633002069845089.785119774
#Sta/Elev= 30
9744.853133.23799806.716 121.7569857.394108.92689878.512105.50519931.59892.18194
9942.21587.53653 9963.4572.479029974.06769.126679995.26370.0453810015.9468.59991
10026.2868.7424410036.6272.0324510046.9572.5331510067.6375.8176510077.9780.96765
10110.6483.1248710119.3283.5020710129.6682.05505   1014079.0939910160.6775.43805
10181.3576.87589 10222.777.5074710243.3879.4020110253.7281.5367110336.4283.50821
10346.7685.3719610367.4486.4931610429.47100.540510450.14107.779110486.55116.5747
#Mann= 3 , 0 , 0
9744.853    0.12       09744.853    0.12       010486.55    0.12       0
#XS Ineff= 2 , 0
       0                 10245.2       0
Bank Sta=9744.853,10486.55
Exp/Cntr=0.3,0.1

Type RM Length L Ch R = 1 ,30827.98,270.336200,270.336200,270.336200
XS GIS Cut Line= 6
868933.045230343845834.559511189868847.122021345845556.205940419
868817.726619003845480.761807945868799.275096487845430.241041824
868785.603814547845382.329263539 868777.22135932 845341.29510604
#Sta/Elev= 30
9634.356106.63659675.75798.111399696.68894.39666 9717.6288.578669728.08587.51666
9738.55187.585319749.016 87.01439769.94882.414719780.41382.606229801.34480.81708
9822.275 80.49449832.74180.649769874.60382.547729895.53582.19673    990679.76593
9916.46678.366039931.52275.489989948.42371.444969969.88467.909639986.686  66.774
10012.77  66.61510023.4267.2935410044.7170.0449310055.3673.2494210065.8777.86369
10076.2780.3859710107.4791.1255810127.93100.066110138.14103.508610152.13105.9859
#Mann= 3 , 0 , 0
9634.356    0.12       09634.356    0.12       010152.13    0.12       0
#XS Ineff= 2 , 0
       0                               0
Bank Sta=9634.356,10152.13
Exp/Cntr=0.3,0.1

Type RM Length L Ch R = 1 ,30557.65,268.179300,268.179300,268.179300
XS GIS Cut Line= 6
868953.856834219845832.899501233869070.698659626 845476.76117392
869076.964856308845454.760518485869108.805816732845344.452922358
 869132.41174668845271.738630919869139.160432824845253.620226192
#Sta/Elev= 30
9585.618103.99939614.98195.26229 9636.0390.264269653.44385.094169678.12779.76827
9717.601 78.76529730.74979.585069783.37280.049729793.89680.68872 9804.4283.80463
9814.94583.730849825.46980.690239835.99479.834279857.043 79.87189867.56781.30284
 9899.1479.981929930.71476.452289951.76370.53114 9983.06 64.66159993.47264.34643
10014.29 64.4828 10024.765.35849 10035.170.3166910048.3278.1558110055.92 83.0621
10076.7498.8602410098.12106.532310118.57116.8411 10139.6 125.173 10193.9152.8087
#Mann= 3 , 0 , 0
9585.618    0.12       09585.618    0.12       0 10193.9    0.12       0
#XS Ineff= 2 , 0
       0                               0
Bank Sta=9585.618,10193.9
Exp/Cntr=0.3,0.1

Type RM Length L Ch R = 1 ,30289.47,249.173300,249.173300,249.173300
XS GIS Cut Line= 6
868968.044552204845842.868748446869118.602313176845694.447974776
869162.302551747845659.402038176869339.820398339845547.828669427
869423.598720264845491.818106259869502.639808699845432.899713946
#Sta/Elev= 30
9562.287104.63189644.34588.514849672.70480.624849686.88477.406529701.06476.16629
9758.43677.346249804.79576.411719845.05578.181169893.06377.892649928.26774.95023
9940.00270.818199963.47265.926549968.133  65.55910010.3666.0632710022.0767.42923
10033.7970.4705410044.5377.36197 10057.787.3407710069.7391.7150910081.7693.21771
10093.7891.1456210105.8194.1308510134.4997.6890810151.6298.5191910166.91 102.717
10179.38108.093410191.85111.781910201.82113.750610218.55115.7106 10238.8116.3179
#Mann= 3 , 0 , 0
9562.287    0.12       09562.287    0.12       0 10238.8    0.12       0
#XS Ineff= 2 , 0
       0                               0
Bank Sta=9562.287,10238.8
Exp/Cntr=0.3,0.1

Type RM Length L Ch R = 1 ,30040.29,249.173300,249.173300,249.173300
XS GIS Cut Line= 6
868984.376730466845887.979199462869244.445622382845822.410789642
869325.089760523845811.725901454869443.926505145845793.170662434
869501.600042839845780.319731304 869504.20698913845779.544474998
#Sta/Elev= 30
 9635.24 98.55979646.19698.325369687.44794.94185 9697.7695.639329728.699 89.4274
9759.63882.037729780.26479.079399790.577 75.69489821.51570.593049831.82870.02726
9852.45471.046159862.76769.62466 9873.0866.875829883.393 68.27819893.70666.74689
9904.00671.019969914.094 72.34969934.269 72.28169954.44366.362549974.61864.00958
9984.70563.02109 10025.262.5677310055.5663.2529810085.9270.1965210096.0473.97366
10126.6692.4187510136.9199.7949810147.15104.3073 10157.4111.247210166.88113.5372
#Mann= 3 , 0 , 0
 9635.24  0.0849       0 9635.24  0.0849       010166.88  0.0849       0
#XS Ineff= 2 , 0
       09803.404                       0
Bank Sta=9635.24,10166.88
Exp/Cntr=0.3,0.1

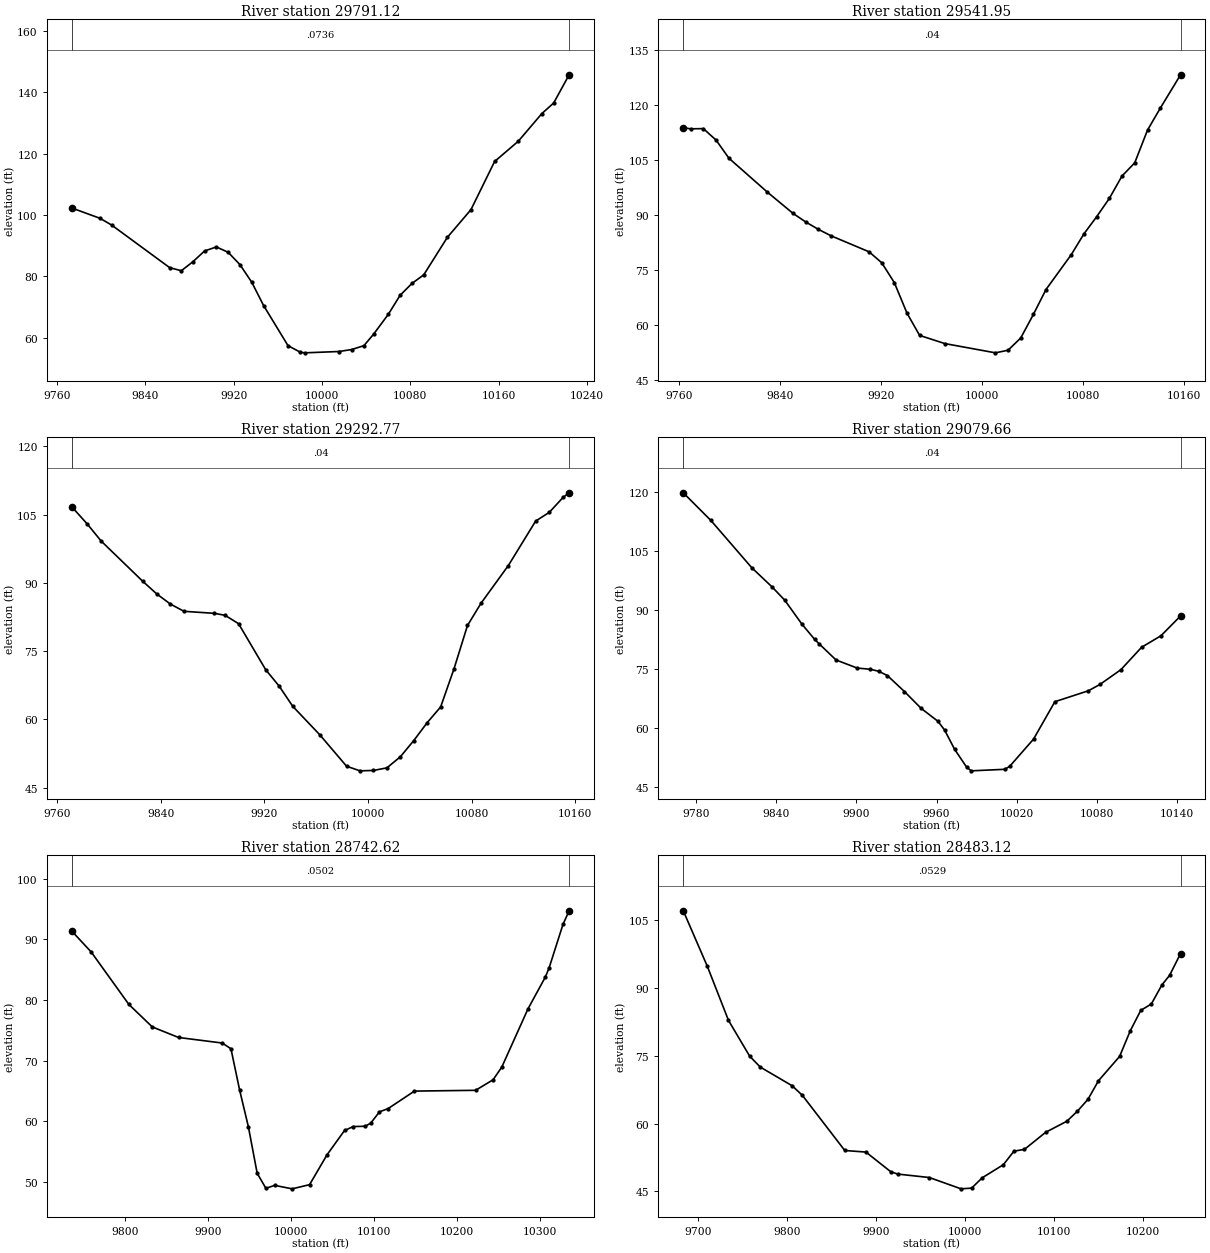
Type RM Length L Ch R = 1 ,29791.12,249.173200,249.173200,249.173200
XS GIS Cut Line= 6
869190.704234484846127.950661796869305.231379671846090.526162408
869353.135254221846072.555865945869426.552508836846032.713607377
869455.040444202846019.260561016869608.075182206845960.918128707
#Sta/Elev= 30
9773.423102.26819798.983 98.91519809.50496.723059862.10682.854699872.62681.87001
9883.14684.804369893.66788.301299904.34489.603359915.02487.875059925.70483.85834
9936.38578.151889947.13970.551549969.29357.485739980.56755.336789984.43455.15831
10015.3255.5896910026.88 56.224110038.0257.4917410046.7461.1951710060.1367.67892
10070.8473.8802510081.5477.7277910092.2480.5295210113.6592.7347310135.05101.7545
10156.45117.404310177.86123.974910199.26132.991710209.96136.429410223.96145.6121
#Mann= 3 , 0 , 0
9773.423  0.0736       09773.423  0.0736       010223.96  0.0736       0
#XS Ineff= 2 , 0
       0                               0
Bank Sta=9773.423,10223.96
Exp/Cntr=0.3,0.1

Type RM Length L Ch R = 1 ,29541.95,249.173300,249.173300,249.173300
XS GIS Cut Line= 6
869219.458350349846309.449057237 869306.67566352846293.872351949
869367.967427394846288.427804659869534.077877341846281.741407579
869570.479246893846278.020936457 869610.72978969846270.987110795
#Sta/Elev= 30
9763.444113.75759769.173113.41529779.322113.4796 9789.47110.33829799.619105.4179
9830.06496.194649850.36190.417149860.419  88.0839870.45886.068169880.498 84.3165
9910.61679.964489920.63276.985439930.63871.566819940.64463.26886 9950.6557.21724
9970.66254.99439 10010.752.4775710020.7153.1933110030.7256.5156410040.7362.91425
10050.7469.7088310070.7679.1865810080.7784.8369710090.8289.4920110100.8794.46752
10110.93100.580110121.02104.166210131.16 113.085 10141.3119.058810157.31128.1234
#Mann= 3 , 0 , 0
9763.444    0.04       09763.444    0.04       010157.31    0.04       0
#XS Ineff= 2 , 0
       0                               0
Bank Sta=9763.444,10157.31
Exp/Cntr=0.3,0.1

Type RM Length L Ch R = 1 ,29292.77,213.111100,213.111100,213.111100
XS GIS Cut Line= 6
869254.029625829846601.405741276869296.530125693 846584.29304412
869357.055804118846563.291585628 869423.44399888846543.234614632
869548.099382651846509.263566623869619.172946582846484.790933914
#Sta/Elev= 30
9771.537106.70999783.363102.97629794.14399.208079826.31990.336579836.90487.61688
9847.48885.366029858.07383.762729881.41983.317849889.71882.888579900.16481.04106
9921.05770.939299931.50467.31209 9941.9562.885129962.75256.647199983.48849.71483
9993.85648.7042610004.2348.7896110014.5949.3582110024.9551.7874910035.3155.35515
10045.6759.2955910056.0462.74005 10066.471.1638910076.7680.6506610087.2485.55331
10108.2993.8280710129.34103.595310139.86105.509610150.66108.836710155.17109.8126
#Mann= 3 , 0 , 0
9771.537    0.04       09771.537    0.04       010155.17    0.04       0
#XS Ineff= 2 , 0
       0                               0
Bank Sta=9771.537,10155.17
Exp/Cntr=0.3,0.1

Type RM Length L Ch R = 1 ,29079.66,337.037600,337.037600,337.037600
XS GIS Cut Line= 6
869377.530903155846868.522818587869433.345944988846820.260355178
869502.723218731846764.740159022869620.085142764846676.453136822
869643.470393335 846657.20455636869666.841909026846634.870378173
#Sta/Elev= 30
9770.471119.87349791.146112.81449821.723100.77979837.01295.851349846.37792.50847
9859.18586.432739868.68282.555779871.99381.43288  9884.877.263319900.69175.19674
9910.41674.900739916.69674.384459923.22473.292619935.96569.225919948.47664.93494
9960.98861.653969965.96359.445629973.49954.514199982.60249.901949986.01149.01056
10011.0349.4006810014.7150.1457110032.5757.0873210048.56 66.633910073.6169.41158
10082.2771.02519   1009874.8035810113.4780.5083210127.9883.44582 10142.688.47881
#Mann= 3 , 0 , 0
9770.471    0.04       09770.471    0.04       0 10142.6    0.04       0
#XS Ineff= 2 , 0
       0                               0
Bank Sta=9770.471,10142.6
Exp/Cntr=0.3,0.1

Type RM Length L Ch R = 1 ,28742.62,259.507500,259.507500,259.507500
XS GIS Cut Line= 2
869896.710852443847167.090239346869707.421790039846597.941123313
#Sta/Elev= 30
9735.37191.352639758.65187.924569804.16679.25626 9832.4275.541989864.036  73.804
9916.72972.885299927.26771.942369937.80665.085829948.345 59.03879958.88351.40494
9969.42248.89923 9979.9649.3950910001.04 48.819310022.1149.5099410043.1954.44083
10064.2758.4488510074.8159.0993410089.3559.1487810095.8859.6682310106.4261.52578
10116.9662.0751610148.5864.9534810222.3565.0817610243.4266.8164510253.9668.91527
10285.5878.5333810306.6683.8212810311.1685.3508810327.7392.4516110335.1794.71506
#Mann= 3 , 0 , 0
9735.371  0.0502       09735.371  0.0502       010335.17  0.0502       0
#XS Ineff= 2 , 0
       0                10070.99       0
Bank Sta=9735.371,10335.17
Exp/Cntr=0.3,0.1

Type RM Length L Ch R = 1 ,28483.12,187.036800,187.036800,187.036800
XS GIS Cut Line= 2
870187.775274787846881.357603109869717.377705739846578.314150766
#Sta/Elev= 30
9683.061107.13189710.15494.828319733.94582.863289757.73674.949159769.63172.53357
9805.58968.386169817.21366.233539864.79554.053679888.58653.702469916.37749.37409
9924.27348.832719959.95948.066319995.64645.5616610007.54 45.722810019.4448.00751
10043.2350.9046210055.12 53.898210067.02 54.309110090.8158.07729 10114.660.52267
 10126.562.7373910138.3965.3678610150.2969.5011910174.0874.8909410185.9780.52753
10197.8785.0765110209.7686.4920810221.6690.7236110230.2892.8287910242.6297.65844
#Mann= 3 , 0 , 0
9683.061  0.0529       09683.061  0.0529       010242.62  0.0529       0
#XS Ineff= 2 , 0
       0                10126.86       0
Bank Sta=9683.061,10242.62
Exp/Cntr=0.3,0.1

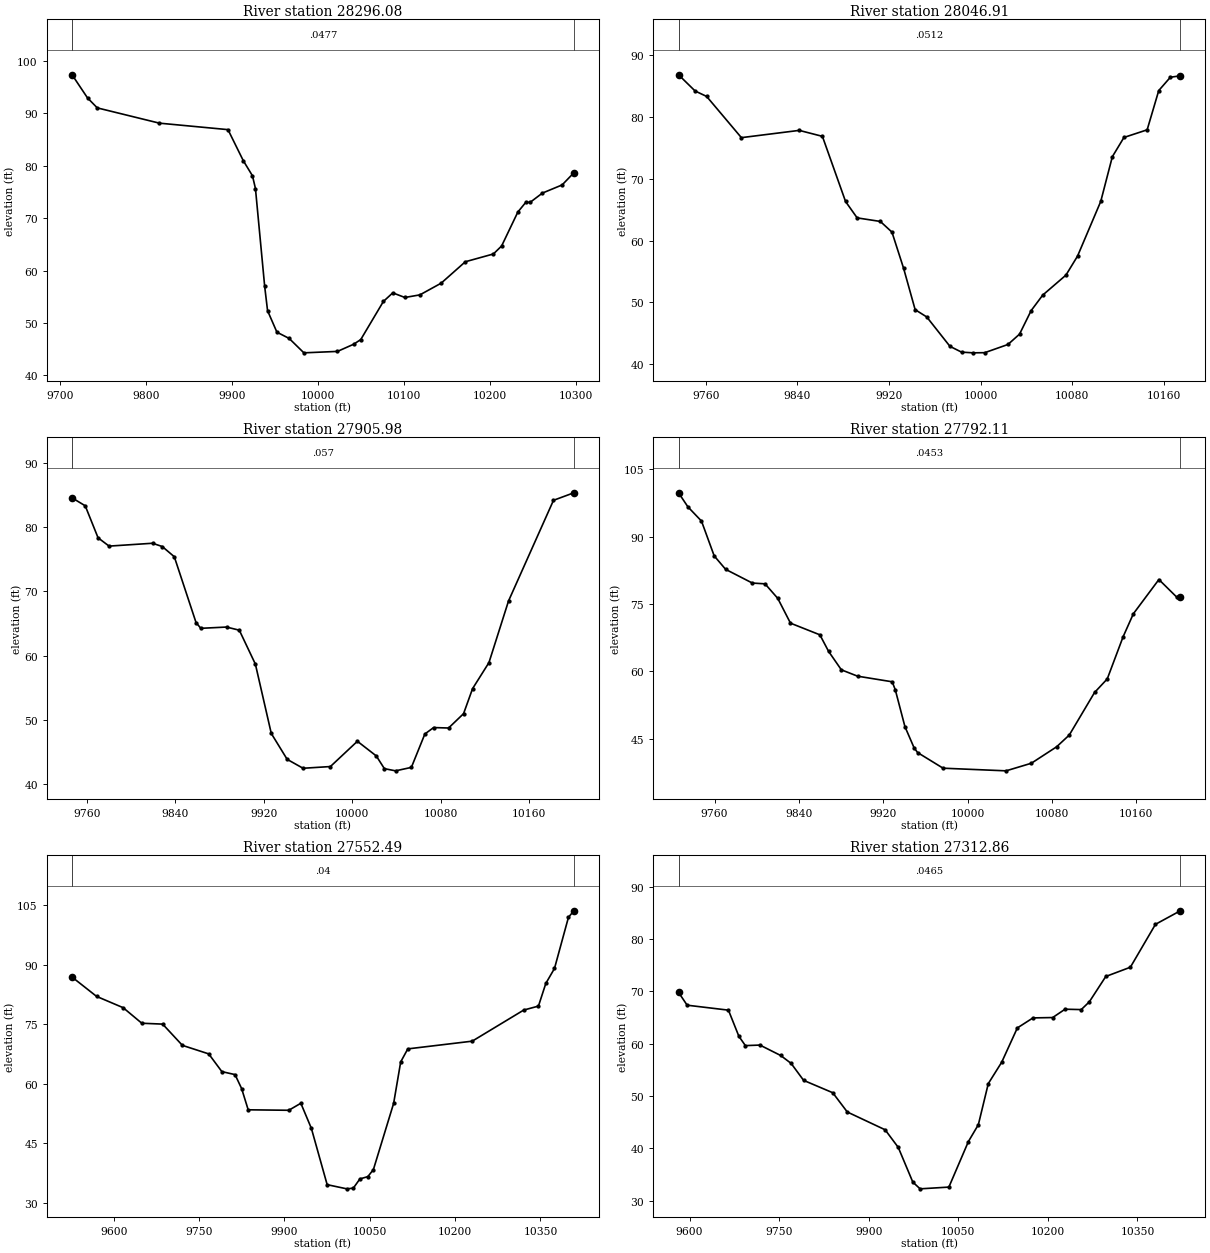
Type RM Length L Ch R = 1 ,28296.08,249.173300,249.173300,249.173300
XS GIS Cut Line= 6
870213.759409257846780.864957378870173.046312403846712.145735323
870108.749466897846636.045194262870034.034190817846562.113493013
869979.882925618846501.958425067869825.288981661846349.304742993
#Sta/Elev= 30
 9714.2497.343329732.202 92.92579743.52491.026249815.72488.111499895.37586.87671
9913.23280.93255 9923.8178.07941  9927.375.640329938.02756.948279941.36952.32977
9952.244 48.22929966.46247.037119983.57344.28981 10022.6 44.563110041.3545.92826
10049.6346.8190610075.9654.0984910086.83  55.73510100.8854.8514310118.3355.34812
10143.0457.5806810171.1561.6707910203.7363.1527910213.3164.6817810232.1971.16529
10241.4273.0150910246.4273.0015510260.6674.7689110283.5876.3266910297.2378.64154
#Mann= 3 , 0 , 0
 9714.24  0.0477       0 9714.24  0.0477       010297.23  0.0477       0
#XS Ineff= 2 , 0
       0                10152.61       0
Bank Sta=9714.24,10297.23
Exp/Cntr=0.3,0.1

Type RM Length L Ch R = 1 ,28046.91,140.927000,140.927000,140.927000
XS GIS Cut Line= 3
870206.628152765 846709.30260125870228.748781308846564.995803667
 870277.11110524846276.395153735
#Sta/Elev= 30
9736.04386.874739750.51384.250999760.62983.36331 9790.9876.688439841.56477.86554
9861.79776.899569882.03166.345399892.17163.689099912.44963.111819922.58961.38428
9932.72855.547159942.86848.818099953.00747.637259973.28642.876259983.42541.93806
9993.56541.82408 10003.741.8505910023.9843.1779410034.1244.8545110044.2648.66608
 10054.451.1814610074.6854.4157810084.8257.50031 10105.1 66.355610115.2473.60336
10125.3876.7202510145.6677.95619 10155.884.3189410165.9486.4724310174.6686.71113
#Mann= 3 , 0 , 0
9736.043  0.0512       09736.043  0.0512       010174.66  0.0512       0
#XS Ineff= 2 , 0
       0                               0
Bank Sta=9736.043,10174.66
Exp/Cntr=0.3,0.1

Type RM Length L Ch R = 1 ,27905.98,113.866600,113.866600,113.866600
XS GIS Cut Line= 5
870217.973996414 846705.24492729870294.646245875846575.457819316
870348.392137708846523.415969267870429.970496046 846466.34811419
870516.827849516846371.410676742
#Sta/Elev= 30
9746.80484.588389758.70383.349619770.31878.360039780.27877.06641  9819.6 77.5122
9828.39176.99768 9839.2675.408729858.92165.147459863.23564.252589886.46464.45031
9898.03963.96046 9912.5858.674629926.95647.865519941.33143.828459955.70742.43907
9980.42442.7078610004.8346.6478710021.9344.3611110029.2442.3793110039.3842.03871
10053.65 42.576510065.8547.7792110073.7448.78338 10087.348.7142210100.8550.95198
   1010954.8530710123.8158.9118810141.5168.5173210182.1784.2053210200.5985.37908
#Mann= 3 , 0 , 0
9746.804   0.057       09746.804   0.057       010200.59   0.057       0
#XS Ineff= 2 , 0
       0                               0
Bank Sta=9746.804,10200.59
Exp/Cntr=0.3,0.1

Type RM Length L Ch R = 1 ,27792.11,239.624000,239.624000,239.624000
XS GIS Cut Line= 6
870300.026220706 846813.03942314870448.785534814  846592.4906528
870457.069049913846579.242546361870458.140804578846577.553952095
870524.972908547846476.529691378870567.000098134846419.031464213
#Sta/Elev= 30
 9725.8799.764399734.76596.62606 9747.6393.463729759.692 85.70289770.53182.70479
9795.87879.64872 9807.9479.472139820.00276.233699832.06570.711929859.94768.11186
9868.25164.409099880.31360.313099895.713 58.89569928.56157.64562 9931.4855.86705
9940.62447.660049949.36342.906729952.68641.87027 9976.8138.3926910036.5737.80308
10060.5539.4957110084.5343.1617310096.5245.77823 10120.5 55.259910132.5558.28483
10147.6567.7111810157.3272.8025410181.54 80.432210198.4876.5098910201.8776.61242
#Mann= 3 , 0 , 0
 9725.87  0.0453       0 9725.87  0.0453       010201.87  0.0453       0
#XS Ineff= 2 , 0
       0                               0
Bank Sta=9725.87,10201.87
Exp/Cntr=0.3,0.1

Type RM Length L Ch R = 1 ,27552.49,239.624000,239.624000,239.624000
XS GIS Cut Line= 6
870423.321325015847112.648890639870674.009886243846680.458819669
870710.102451603846623.888108709870776.696391628846534.803918341
 870879.24309641846409.926343412870907.541316323846377.866916547
#Sta/Elev= 30
 9526.5286.902359569.61482.041059616.36479.193779649.12975.278939685.78875.05841
  9720.569.708289766.78267.559419789.92463.090639813.06562.341029824.63558.83147
9836.20653.474699907.55353.353619928.77155.123039947.31148.797029975.05334.61699
10009.5933.5657610020.99 33.736610032.6436.06517 10046.636.6426710056.3638.41623
10091.9555.1020410104.3665.5391910116.8568.8180910230.1270.7617910320.69 78.5981
10346.57 79.595510359.5185.2997810374.78 89.080610399.32101.952910408.84103.6056
#Mann= 3 , 0 , 0
 9526.52    0.04       0 9526.52    0.04       010408.84    0.04       0
#XS Ineff= 2 , 0
       0                               0
Bank Sta=9526.52,10408.84
Exp/Cntr=0.3,0.1

Type RM Length L Ch R = 1 ,27312.86,239.624000,239.624000,239.624000
XS GIS Cut Line= 6
870607.235061989847196.825954033870863.657742286846827.218292636
870906.857503881846769.807117802870961.929210429846704.583426603
 871043.27404593846615.645993435871122.085459385846535.285387414
#Sta/Elev= 30
9581.58469.833989595.99867.377759665.13166.430149682.62261.425729693.50659.64498
9717.88359.746099752.586 57.75539770.07756.242869791.01352.993299839.767 50.6275
9864.14446.939789927.49843.534919949.46340.16483 9973.8433.525229986.02832.23374
10034.2232.5674310066.9441.2922810083.5744.50776 10100.252.3703510122.6756.46479
10148.8563.0252410175.0264.9458110208.0265.0140310228.7566.6103110255.8566.53738
 10269.468.0240610296.9372.87255 10338.174.6439210380.1282.8549410421.7485.44721
#Mann= 3 , 0 , 0
9581.584  0.0465       09581.584  0.0465       010421.74  0.0465       0
#XS Ineff= 2 , 0
       09928.216                       0
Bank Sta=9581.584,10421.74
Exp/Cntr=0.3,0.1

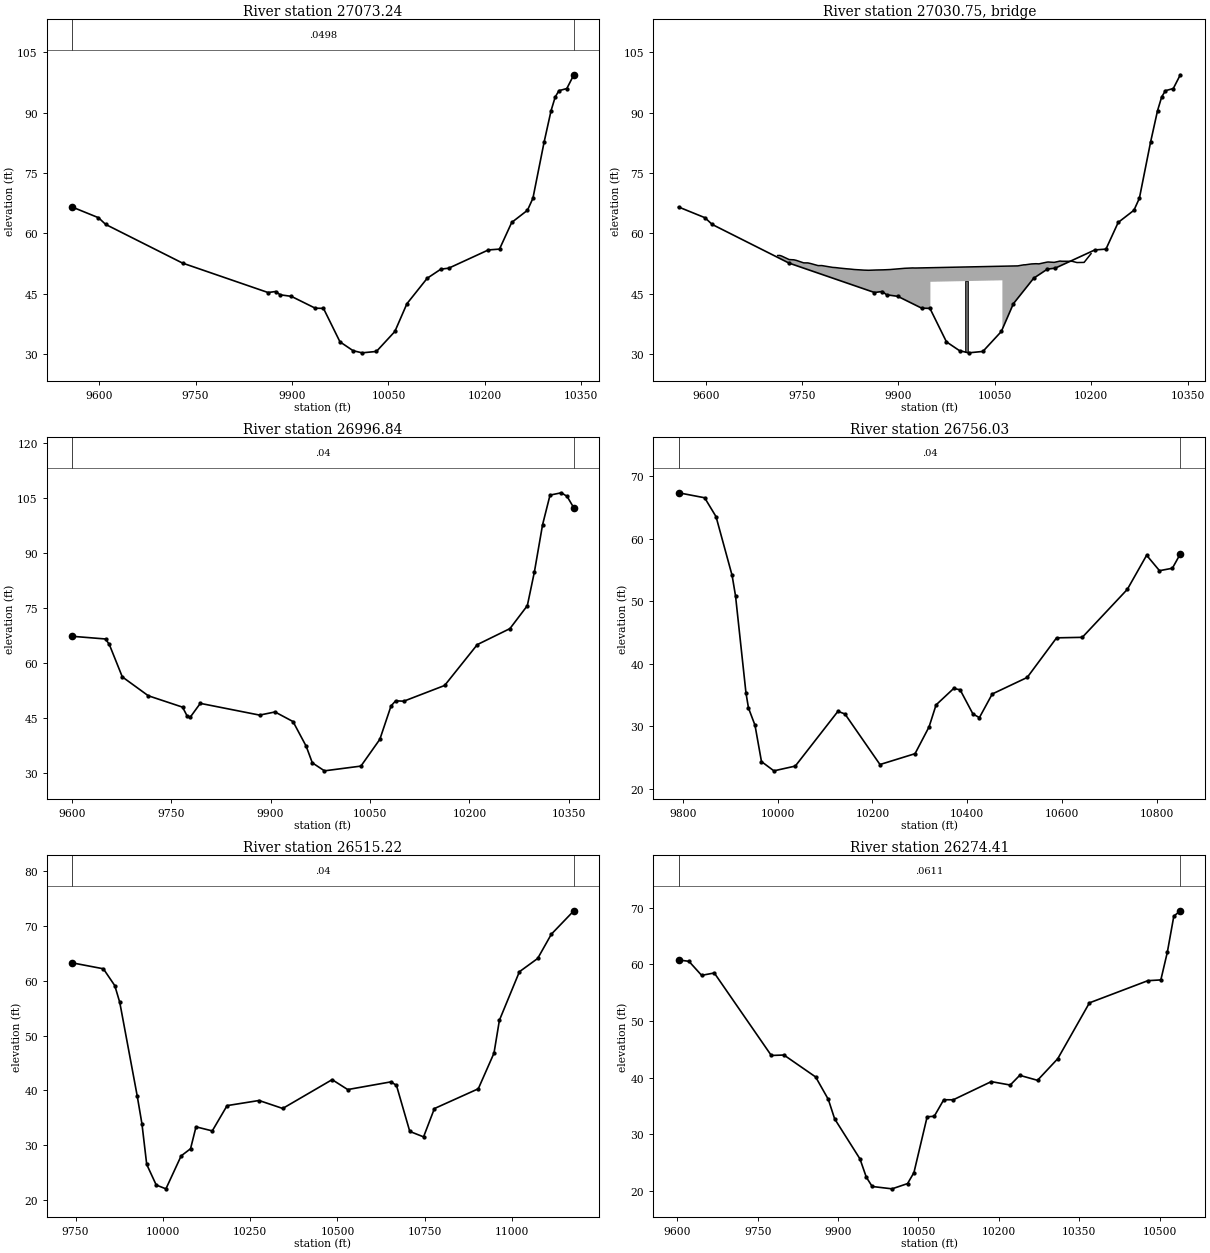
Type RM Length L Ch R = 1 ,27073.24,76.405600,76.405600,76.405600
XS GIS Cut Line= 6
870670.113257777847252.652991874870774.175137693847187.879998142
870972.426440441 847053.38584403871019.531517643 847015.45334454
871110.091421695846922.373215641871241.763162489846736.045424919
#Sta/Elev= 30
 9557.8466.572289598.93263.912399610.16962.242859729.74652.64997 9862.6745.35413
9874.75445.60551 9881.4844.792159898.922 44.40439936.12441.467849948.96341.41434
9974.64233.110759995.04430.92011   1000930.3883710031.3230.73472   1006035.68327
10078.76 42.569810110.3348.89213 10131.651.1502210143.8451.3940310205.4755.91646
 10222.856.12036 10241.862.7349910266.2965.7549710274.7868.7309110292.1182.60615
10303.0390.4723610309.4493.8541810315.2795.4228110327.5295.9555910338.4899.37024
#Mann= 3 , 0 , 0
 9557.84  0.0498       0 9557.84  0.0498       010338.48  0.0498       0
#XS Ineff= 2 , 0
       09924.748        10084.98       0
Bank Sta=9557.84,10338.48
Exp/Cntr=0.3,0.1

Type RM Length L Ch R = 3 ,27030.75,,,
BEGIN DESCRIPTION:
END DESCRIPTION:
Bridge Culvert--1,0,-1,-1, 0
Deck Dist Width WeirC Skew NumUp NumDn MinLoCord MaxHiCord MaxSubmerge Is_Ogee
21.202800,34.000000,2.6,0, 54, 54, , , 0.95, 0, 0,0,,
 9712.09 9715.47 9718.69 9729.95 9737.24 9741.21 9752.47 9759.00 9763.73 9774.99
 9780.76 9786.25 9797.51 9802.52 9808.77 9820.02 9824.29 9831.28 9842.54 9846.05
 9853.80 9865.06 9867.81 9875.92 9876.33 9887.76 9888.86 9899.20 9909.47 9910.63
 9922.07 9926.02 9949.66 9949.6610061.6610061.6610085.6110094.5710095.5710096.83
10106.6910113.9410118.5210130.3510132.6610142.1810151.3710154.0110165.8410170.09
10177.6710188.8110189.5010199.57
   54.53   54.55   54.37   53.53   53.47   53.32   52.71   52.70   52.53   52.03
   52.04   51.89   51.59   51.53   51.41   51.23   51.18   51.06   50.95   50.91
   50.87   50.94   50.95   50.98   50.98   51.06   51.08   51.22   51.36   51.37
   51.45   51.43   51.51   51.51   51.88   51.88   51.96   52.21   52.23   52.22
   52.44   52.50   52.46   52.87   52.93   52.83   53.16   53.11   53.10   53.10
   52.79   52.82   52.97   54.99
 -945.47 -945.45 -945.63 -946.47 -946.53 -946.68 -947.29 -947.30 -947.47 -947.97
 -947.96 -948.11 -948.41 -948.47 -948.59 -948.77 -948.82 -948.94 -949.05 -949.09
 -949.13 -949.06 -949.05 -949.02 -949.02 -948.94 -948.92 -948.78 -948.64 -948.63
 -948.55 -948.57 -948.49   48.01   48.38 -948.12 -948.04 -947.79 -947.77 -947.78
 -947.56 -947.50 -947.54 -947.13 -947.07 -947.17 -946.84 -946.89 -946.90 -946.90
 -947.21 -947.18 -947.03 -945.01
 9712.09 9715.47 9718.69 9729.95 9737.24 9741.21 9752.47 9759.00 9763.73 9774.99
 9780.76 9786.25 9797.51 9802.52 9808.77 9820.02 9824.29 9831.28 9842.54 9846.05
 9853.80 9865.06 9867.81 9875.92 9876.33 9887.76 9888.86 9899.20 9909.47 9910.63
 9922.07 9926.02 9951.76 9951.7610063.7610063.7610085.6110094.5710095.5710096.83
10106.6910113.9410118.5210130.3510132.6610142.1810151.3710154.0110165.8410170.09
10177.6710188.8110189.5010199.57
   54.53   54.55   54.37   53.53   53.47   53.32   52.71   52.70   52.53   52.03
   52.04   51.89   51.59   51.53   51.41   51.23   51.18   51.06   50.95   50.91
   50.87   50.94   50.95   50.98   50.98   51.06   51.08   51.22   51.36   51.37
   51.45   51.43   51.52   51.52   51.89   51.89   51.96   52.21   52.23   52.22
   52.44   52.50   52.46   52.87   52.93   52.83   53.16   53.11   53.10   53.10
   52.79   52.82   52.97   54.99
 -945.47 -945.45 -945.63 -946.47 -946.53 -946.68 -947.29 -947.30 -947.47 -947.97
 -947.96 -948.11 -948.41 -948.47 -948.59 -948.77 -948.82 -948.94 -949.05 -949.09
 -949.13 -949.06 -949.05 -949.02 -949.02 -948.94 -948.92 -948.78 -948.64 -948.63
 -948.55 -948.57 -948.48   48.02   48.39 -948.11 -948.04 -947.79 -947.77 -947.78
 -947.56 -947.50 -947.54 -947.13 -947.07 -947.17 -946.84 -946.89 -946.90 -946.90
 -947.21 -947.18 -947.03 -945.01
Pier Skew, UpSta & Num, DnSta & Num=  ,10005.66, 2 ,10007.76, 2 , 0 , 0 , 0 ,,
    4.00    4.00
 -948.31   51.69
    4.00    4.00
 -948.30   51.70
BR Coef=-1 , 0 , 0 ,, 0 ,,,0.8,0,1,0,
WSPro=,,,, 1 ,,,, 0 ,,,, 0 ,,,,-1 ,-1 ,-1 , 0 , 0 , 0 , 0 , 0
BC Design=,, 0 ,, 0 ,,,,,,

Type RM Length L Ch R = 1 ,26996.84,240.806900,240.806900,240.806900
XS GIS Cut Line= 5
870751.599403927847283.647464725871021.638060604847123.592183353
871039.007429783847105.219431017871125.854426392 847013.35566132
871295.981883905846776.669825358
#Sta/Elev= 30
9600.60267.230389651.05366.495339656.78765.000299676.39956.153519715.62451.00668
9767.29947.902049774.46245.402429778.923 45.16569794.07448.934249883.54545.73224
9906.79446.58772 9933.9643.975149953.85737.232629963.07332.71695 9981.3830.52915
10036.4331.8245710064.9739.1272810081.8848.2361310088.8249.6266610101.1349.52618
10162.7153.8129310211.9764.9551710261.2369.3194210287.4875.5742210298.18 84.8098
10310.4997.6607710321.75105.741510338.88 106.37310347.44105.3906 10357.7102.2459
#Mann= 3 , 0 , 0
9600.602    0.04       09600.602    0.04       0 10357.7    0.04       0
#XS Ineff= 2 , 0
       09926.364        10087.66       0
Bank Sta=9600.602,10357.7
Exp/Cntr=0.3,0.1

Type RM Length L Ch R = 1 ,26756.03,240.807000,240.807000,240.807000
XS GIS Cut Line= 6
 871078.52105683847393.579884464871136.284008344847336.918488375
871213.991626905847264.249842602871229.487682739847250.380565133
871308.267187271847180.442025956871857.385331736846676.579466443
#Sta/Elev= 30
9790.89867.340919845.99166.542779870.01363.522859903.902 54.12189911.12850.85348
9933.183 35.3168 9938.5132.903459952.20230.153799965.89324.335729992.07322.85652
10037.2323.6174910127.1932.3757310141.9831.9566810215.9323.8663710289.8925.60202
10319.4729.8921510334.2633.4055510371.3536.0303210384.9235.8309310412.0631.95356
10425.6431.3683910452.7835.1521710526.5437.79829 10588.544.1325710642.7944.21543
10737.7951.8916710778.5157.3465710805.65 54.877510832.7955.26805 10849.657.55931
#Mann= 3 , 0 , 0
9790.898    0.04       09790.898    0.04       0 10849.6    0.04       0
#XS Ineff= 2 , 0
       0                10142.07       0
Bank Sta=9790.898,10849.6
Exp/Cntr=0.3,0.1

Type RM Length L Ch R = 1 ,26515.22,240.806900,240.806900,240.806900
XS GIS Cut Line= 6
871217.138570942847606.727875852871270.335512786847557.061157027
871319.714604662847506.619131322871399.658827923847420.336838737
871440.365831601847377.428024483872294.253740299846657.585352695
#Sta/Elev= 30
    974063.275859829.66562.18678 9862.3459.112429876.63556.043769926.48339.01272
9940.11733.89864 9953.7526.501179981.01722.7384710008.7622.0412410052.3528.05094
10079.2929.3603610094.9433.3528710141.4932.6116110183.9237.2245710275.4838.15722
10343.1836.7051710484.7441.9612510529.3640.1517110653.4841.5611510668.9940.90801
10707.0932.5178510746.5731.52248 10777.636.6871610903.2840.2951310948.2646.80207
10963.7752.80167   1102161.6463511073.3164.0683911112.5568.5020211176.9772.76999
#Mann= 3 , 0 , 0
    9740    0.04       0    9740    0.04       011176.97    0.04       0
#XS Ineff= 2 , 0
       0                10233.08       0
Bank Sta=9740,11176.97
Exp/Cntr=0.3,0.1

Type RM Length L Ch R = 1 ,26274.41,236.230700,236.230700,236.230700
XS GIS Cut Line= 5
871238.560374813847797.572772652871574.243055309847586.117577766
871575.656983574847584.703079008871607.415466539847554.489870508
872015.028476155847275.936399765
#Sta/Elev= 30
9602.26860.755899621.69860.510369645.33558.038389668.97258.45848 9775.3443.91286
9798.97743.988519858.07140.124449881.70836.171429893.52732.739949940.80125.66931
 9952.62 22.45159963.57320.8124110000.5820.3958110029.5921.32108 10041.523.26387
10066.1333.1000610079.3833.19062 10097.136.1024510114.8336.0949610185.7239.29968
10221.1738.6988610238.8940.4113710272.0439.5299510309.7943.3366810368.9353.18804
10477.9457.0985310502.1657.2339710514.2862.1105610526.3968.4773610538.5369.42327
#Mann= 3 , 0 , 0
9602.268  0.0611       09602.268  0.0611       010538.53  0.0611       0
#XS Ineff= 2 , 0
       0                10198.42       0
Bank Sta=9602.268,10538.53
Exp/Cntr=0.3,0.1

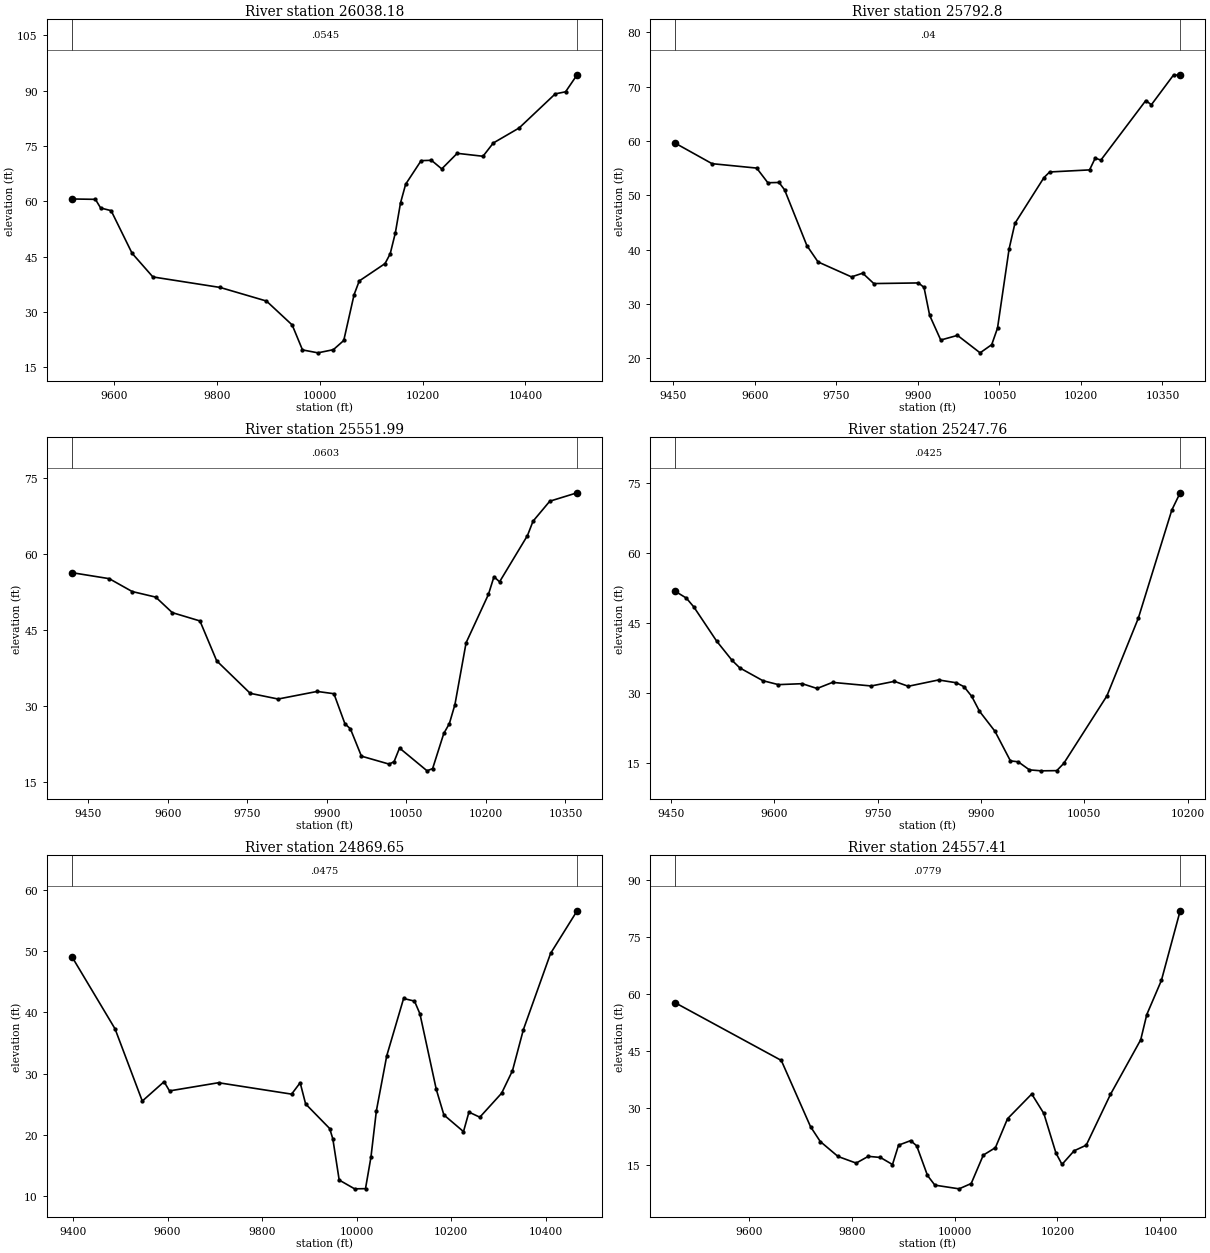
Type RM Length L Ch R = 1 ,26038.18,245.383200,245.383200,245.383200
XS GIS Cut Line= 6
871200.734593493847845.531476509871318.602009501847822.427917745
871432.443122437847806.093603835871703.075309235847790.326082214
871734.570283459847785.814760872872177.405607846847747.740374451
#Sta/Elev= 30
 9517.9760.611599563.07860.514719573.26858.164829593.64957.44604 9634.4145.88702
9674.94339.454639805.76836.602129895.92132.91373    994626.418889966.03219.65133
9996.07918.8563210026.1419.7144710046.3522.2091510066.4834.6606810076.5138.36757
10126.6743.07955 10136.745.7279410146.7451.4056210156.7759.51798 10166.864.62234
 10196.971.0124810216.9671.1107410237.0268.7767210267.1273.0031110317.2872.20354
10337.3575.8036810387.5879.87689 10457.989.1377210477.9989.69907 10500.594.31862
#Mann= 3 , 0 , 0
 9517.97  0.0545       0 9517.97  0.0545       0 10500.5  0.0545       0
#XS Ineff= 2 , 0
       0                               0
Bank Sta=9517.97,10500.5
Exp/Cntr=0.3,0.1

Type RM Length L Ch R = 1 , 25792.8,240.806900,240.806900,240.806900
XS GIS Cut Line= 6
871058.999347646  847889.1214118871590.574841757848012.520805434
871716.233301562848059.456227063871781.881591896848080.931865394
871855.804064453848101.725673076871956.600078434848125.553683134
#Sta/Elev= 30
 9453.2959.604149521.04555.834079603.17255.020989623.70452.324449644.23652.37362
9654.50251.025049695.566 40.75269716.09737.749319777.69334.993699798.22535.68004
9818.75633.767969900.88433.88274 9911.1533.058719921.51827.909759941.94723.37308
9972.74524.2313610014.3621.0168210035.7222.5210910046.3925.5631410067.75 40.1529
10078.43 44.842110131.8353.2615310142.3754.3060710215.8454.6888710226.2356.85807
10236.6256.4899510319.2867.4503210329.5666.6757110370.6672.1954510382.5872.07373
#Mann= 3 , 0 , 0
 9453.29    0.04       0 9453.29    0.04       010382.58    0.04       0
#XS Ineff= 2 , 0
       0                               0
Bank Sta=9453.29,10382.58
Exp/Cntr=0.3,0.1

Type RM Length L Ch R = 1 ,25551.99,304.235700,304.235700,304.235700
XS GIS Cut Line= 6
870961.824762459848080.582576079871055.924080883848100.454406823
871171.607048637848132.722552767871433.754240591848219.064564472
871610.281961136 848265.17118048871874.056791013848351.461746224
#Sta/Elev= 30
9419.86256.337139489.63955.160749532.95552.615179577.36851.510789608.51348.44518
9660.76546.79563 9692.3538.903199755.52132.482139808.16331.353749881.862 32.8554
9913.42832.403799934.17526.463129944.54925.449719965.29620.05385 10017.618.47852
 10026.918.9715410037.1721.6592510089.1417.14987 10099.617.5989510120.6424.54312
10131.1626.4885210141.6830.2659210162.7342.4828710204.8152.0349910215.3355.54931
10225.8554.5322410278.4663.6827910288.9866.5285310320.5570.4802410372.1672.14742
#Mann= 3 , 0 , 0
9419.862  0.0603       09419.862  0.0603       010372.16  0.0603       0
#XS Ineff= 2 , 0
       0                               0
Bank Sta=9419.862,10372.16
Exp/Cntr=0.3,0.1

Type RM Length L Ch R = 1 ,25247.76,378.106800,378.106800,378.106800
XS GIS Cut Line= 6
870910.405230133848273.712088127870973.481479403 848302.75084968
871364.534698863848502.432102313871366.311144162848503.350926033
871414.062047494 848527.53274296871565.886170475848601.670515024
#Sta/Elev= 30
 9456.0751.816469472.13750.361829483.06348.460119516.17341.157839538.44337.05936
9549.67135.438269583.35632.686919605.81331.849519640.40232.049149661.95431.02469
 9684.4132.328919740.55231.562429774.23732.549449794.32731.496299838.30532.84908
9864.06332.248219875.29131.406439886.51929.333529897.74726.155929920.20421.87125
 9942.6615.538179953.88915.343849970.24413.615919987.54313.4085710009.9613.45329
10020.1215.0096810082.7229.43627 10128.346.0485910176.9669.1953510189.0872.88394
#Mann= 3 , 0 , 0
 9456.07  0.0425       0 9456.07  0.0425       010189.08  0.0425       0
#XS Ineff= 2 , 0
       09595.524                       0
Bank Sta=9456.07,10189.08
Exp/Cntr=0.3,0.1

Type RM Length L Ch R = 1 ,24869.65,312.245400,312.245400,312.245400
XS GIS Cut Line= 2
870884.518701532848306.306061865871415.003161931849233.750724293
#Sta/Elev= 30
9398.15849.017159488.81637.302619546.417 25.50529592.49828.666559604.01927.16726
9707.701 28.50359862.367 26.63869880.50528.500129892.02525.037689942.93121.01504
9949.62719.324459963.07212.595119995.70811.1575910018.7511.1891710030.2716.33178
10041.7923.9265810063.7832.9293210099.3942.2740310122.4341.8434310133.9539.75975
10168.5127.4168110184.6223.2424410226.1120.5126310237.63 23.701610260.6722.86813
10306.7626.78866 10329.830.4769410352.8437.1827710410.4449.65058 10466.656.61081
#Mann= 3 , 0 , 0
9398.158  0.0475       09398.158  0.0475       0 10466.6  0.0475       0
#XS Ineff= 2 , 0
       09522.458        10118.99       0
Bank Sta=9398.158,10466.6
Exp/Cntr=0.3,0.1

Type RM Length L Ch R = 1 ,24557.41,209.446800,209.446800,209.446800
XS GIS Cut Line= 2
870606.210961061848476.160958448871124.240443864849310.175503915
#Sta/Elev= 30
9456.739 57.63059662.92242.45781 9719.7825.015879738.73321.099979773.21617.16699
9808.53215.420089832.07617.19997 9855.6216.907529879.16415.044099890.93620.14093
 9914.4821.340079926.25219.959639947.21212.161989961.568 9.6167310008.668.644455
 10032.210.0453710055.7417.5258810079.2919.4882110102.8327.1043710149.9233.61357
10173.4628.4818510197.0118.0609910208.7815.0786810232.3218.6603110255.8720.13801
10302.9633.5039410361.8247.8891310373.59 54.517210402.0763.5356610438.5481.85707
#Mann= 3 , 0 , 0
9456.739  0.0779       09456.739  0.0779       010438.54  0.0779       0
#XS Ineff= 2 , 0
       09666.182        10288.44       0
Bank Sta=9456.739,10438.54
Exp/Cntr=0.3,0.1