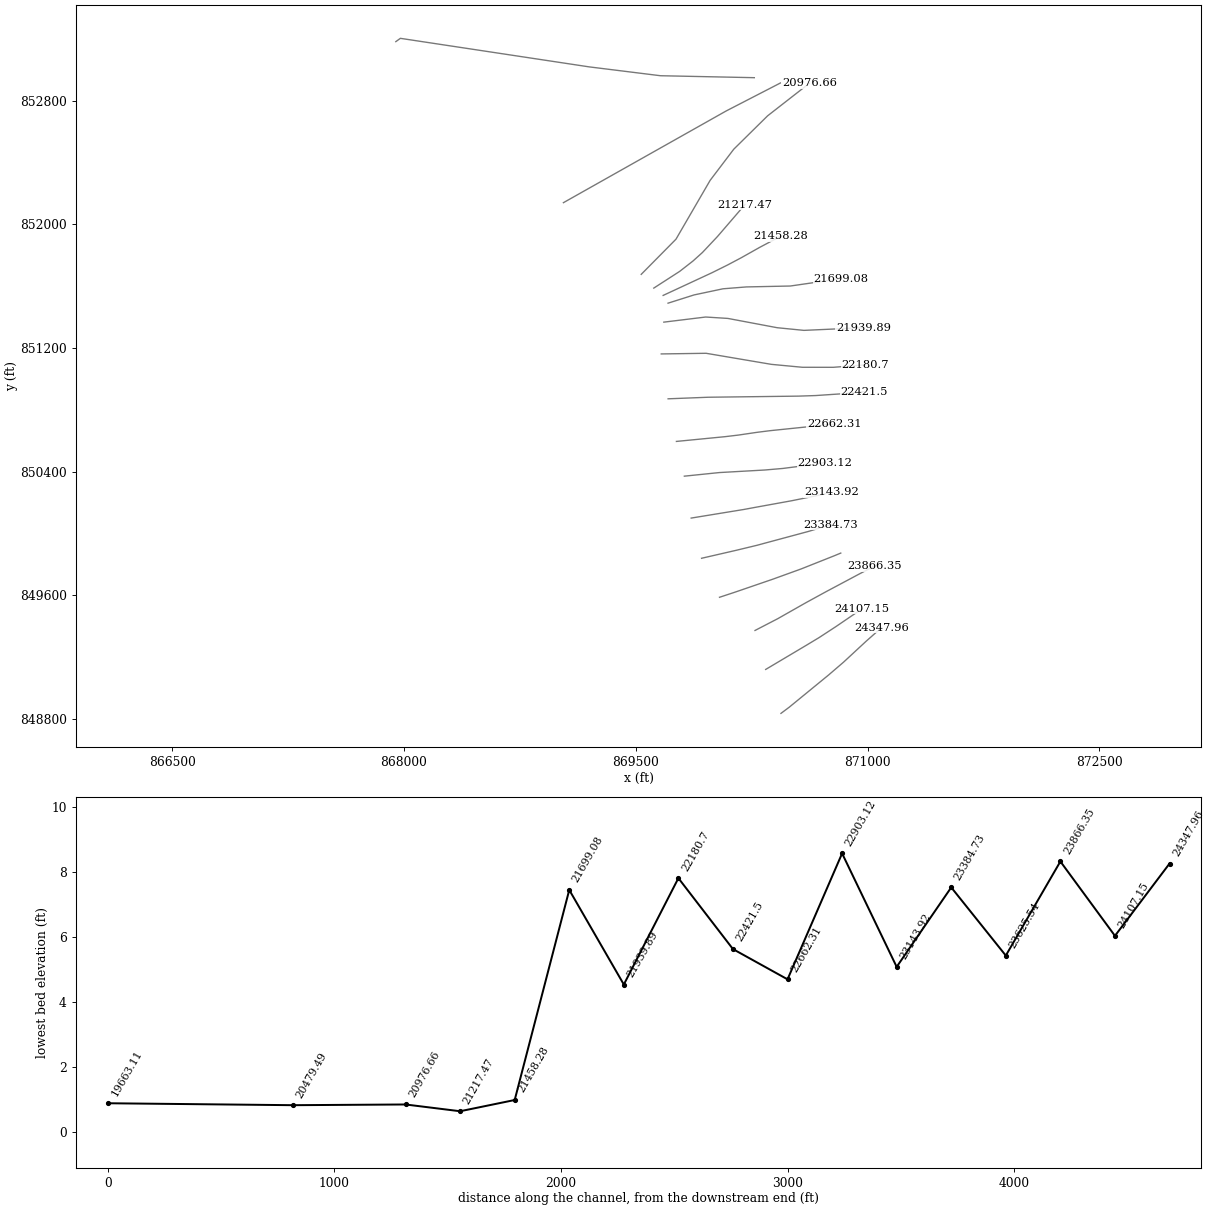
HEC-RAS study 16857_ras.prj: 16857

--- 16857_ras.g01 (geometry) --- (continued)

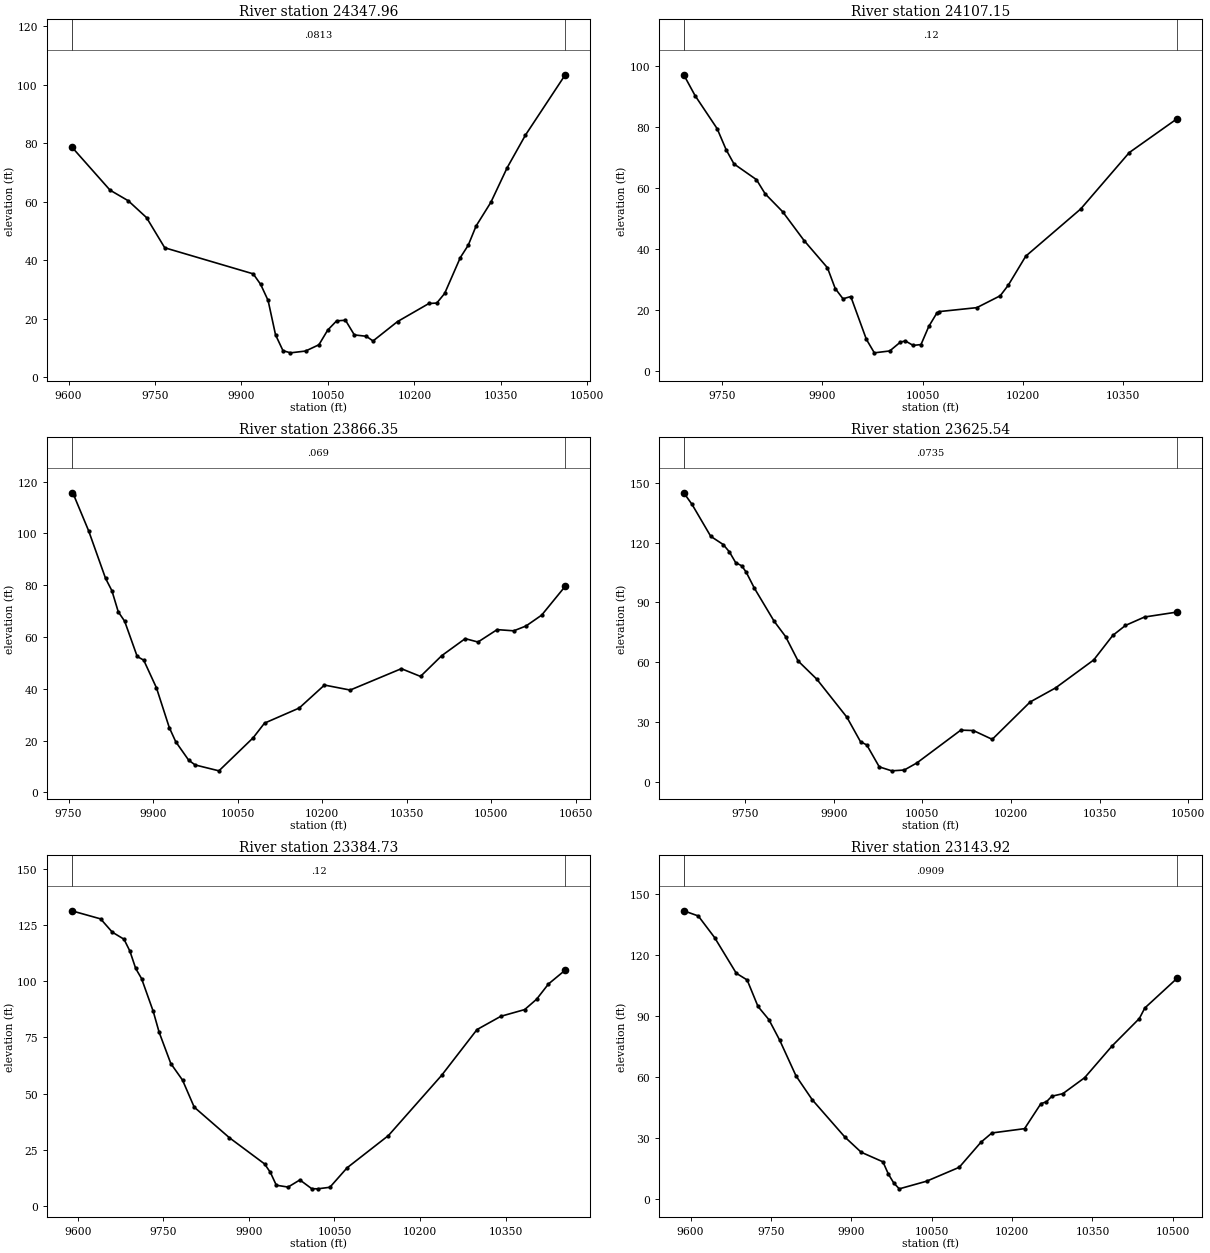
Type RM Length L Ch R = 1 ,24347.96,240.806900,240.806900,240.806900
XS GIS Cut Line= 6
870439.354745689848835.120686329870492.692043552848874.976964659
870747.327743752849083.320780467870843.880028585849166.103453099
870991.531341587849302.896156325871090.635113714 849390.35181275
#Sta/Elev= 30
9605.40778.712589671.99163.900749703.636 60.26319735.24554.526599766.85344.19735
9920.33335.279289933.24731.67801 9946.1626.181689959.07414.421539971.9889.011032
9984.9648.27279610011.118.88204110034.3111.0346110049.6716.0816210065.0319.20733
 10080.419.4205510095.7614.4050610116.4913.9373410128.1812.33004 10170.718.96828
10225.1325.1469410238.7725.29708 10252.428.5701310279.6640.8690110293.2945.05004
10306.9351.6311110332.6259.7535310360.9571.6054310392.6182.7292110461.65103.3476
#Mann= 3 , 0 , 0
9605.407  0.0813       09605.407  0.0813       010461.65  0.0813       0
#XS Ineff= 2 , 0
       0                               0
Bank Sta=9605.407,10461.65
Exp/Cntr=0.3,0.1

Type RM Length L Ch R = 1 ,24107.15,240.807000,240.807000,240.807000
XS GIS Cut Line= 6
870340.434251558849119.585520093870345.622221958849122.548987683
 870605.03556466849276.775411467870686.864656846849326.121234206
870795.487795897849397.101015019870964.362654378849512.171009868
#Sta/Elev= 30
9693.22996.980919710.11490.180789743.13779.358299756.64972.432369768.28267.82659
9801.84262.690469814.81858.063249840.97952.205459872.987  42.7789907.88833.87963
9919.52227.082259931.15623.728389942.78924.453139966.05710.473649977.9586.048895
10000.966.66336510016.939.56902610024.319.93766510035.998.47054310047.678.760617
10059.35 14.707510071.0218.9390510075.0219.5387710131.07 20.8272   1016624.70793
10177.95 28.135110204.1937.6647310286.2353.0889710358.8371.5419210430.6782.67502
#Mann= 3 , 0 , 0
9693.229    0.12       09693.229    0.12       010430.67    0.12       0
#XS Ineff= 2 , 0
       0                               0
Bank Sta=9693.229,10430.67
Exp/Cntr=0.3,0.1

Type RM Length L Ch R = 1 ,23866.35,240.806900,240.806900,240.806900
XS GIS Cut Line= 6
870271.401184467849371.736778333870417.551568748849447.438880741
870598.604919539 849550.15523249870726.180586679849620.016049728
870952.771561663849740.728601172 871042.19629793849787.085423529
#Sta/Elev= 30
 9755.42115.70199759.404 114.6719785.523101.02679815.53482.665669826.82477.87388
9838.11469.722429849.40566.12322 9871.6952.499089883.27551.065669905.85640.38632
9928.57925.06358 9940.0619.579419963.02212.449469974.50310.6137510016.698.338718
10077.3421.0874910097.55 26.7558 10159.132.5885810203.8941.4627410249.4939.52785
10340.2847.7810310374.2844.7975510411.8552.7925110453.5959.3841110476.25  58.075
10510.2462.8647410539.6662.4030610561.3964.2587810589.2168.45658 10631.179.62212
#Mann= 3 , 0 , 0
 9755.42   0.069       0 9755.42   0.069       0 10631.1   0.069       0
#XS Ineff= 2 , 0
       0                               0
Bank Sta=9755.42,10631.1
Exp/Cntr=0.3,0.1

Type RM Length L Ch R = 1 ,23625.54,240.807000,240.807000,240.807000
XS GIS Cut Line= 6
870041.628195098 849586.50823503870142.069277748849619.680549214
870385.931590288849703.337145984870570.243560916849770.047869545
870785.931672109849855.701390497870826.327175189849872.568136742
#Sta/Elev= 30
 9646.23145.07719660.312 139.2129691.906123.21119712.968119.10079723.499115.4055
9734.031110.02689744.562108.35159752.007105.16069765.67997.216339799.17180.58551
9818.54572.892759839.69260.647559871.41251.478929922.32132.381019945.42520.05231
9955.99818.450779977.144 7.440239998.2915.44090410019.465.85210310040.739.395576
10115.1825.8875310136.4525.6741710168.3521.2555310232.4740.0113410275.5147.08233
10340.0761.1153210372.3573.4361410393.8678.4656610426.1482.6908910481.6885.20164
#Mann= 3 , 0 , 0
 9646.23  0.0735       0 9646.23  0.0735       010481.68  0.0735       0
#XS Ineff= 2 , 0
       0                               0
Bank Sta=9646.23,10481.68
Exp/Cntr=0.3,0.1

Type RM Length L Ch R = 1 ,23384.73,240.806900,240.806900,240.806900
XS GIS Cut Line= 6
869925.512093955849838.961263584870145.550110083849889.553145037
870285.235135306849923.177962081870326.262794018849934.366213519
870615.856810575850012.306600487 870763.20300743850056.738282737
#Sta/Elev= 30
 9589.02131.39629639.799 127.7849660.321121.86129680.843 118.7259691.104113.4639
9701.364105.68599711.625101.19749732.14786.556749742.40877.32078 9762.93 63.3551
9783.45255.983629803.97443.932449865.661 30.30939927.37518.641629937.661  14.823
9947.9479.1539929968.5948.3297039989.32311.5101310010.057.609519 10020.47.540313
10041.928.23657810072.1816.9282710144.67 31.285710237.8858.0786510300.0178.48513
10341.7884.3931510383.5687.3845610404.4591.9818910425.3498.79931 10454.8104.9766
#Mann= 3 , 0 , 0
 9589.02    0.12       0 9589.02    0.12       0 10454.8    0.12       0
#XS Ineff= 2 , 0
       0                               0
Bank Sta=9589.02,10454.8
Exp/Cntr=0.3,0.1

Type RM Length L Ch R = 1 ,23143.92,240.806900,240.806900,240.806900
XS GIS Cut Line= 6
869858.239635391850099.083317598870200.070156628850154.979461038
870266.204692411850167.269718559870510.074465947850211.523044959
870696.017680065850249.331398054870764.153016973850264.972861824
#Sta/Elev= 30
9587.363141.86469614.478139.31629644.877 128.7119685.408111.13299705.674107.8337
9725.939 94.78849746.20588.335779766.47178.178439796.86960.649449827.268 48.8716
9888.06430.556449918.46323.099719959.08918.37616 9969.2612.321559979.4327.907666
9989.603   5.09310040.438.83824710101.4115.6833310142.0628.0465810162.3932.57373
10223.37 34.696810253.8847.0062310264.0847.8838810274.29 50.6413 10294.751.89029
10335.5259.7662110386.5475.3365610437.5688.8729810447.8294.0552810508.51108.7744
#Mann= 3 , 0 , 0
9587.363  0.0909       09587.363  0.0909       010508.51  0.0909       0
#XS Ineff= 2 , 0
       0                10168.86       0
Bank Sta=9587.363,10508.51
Exp/Cntr=0.3,0.1

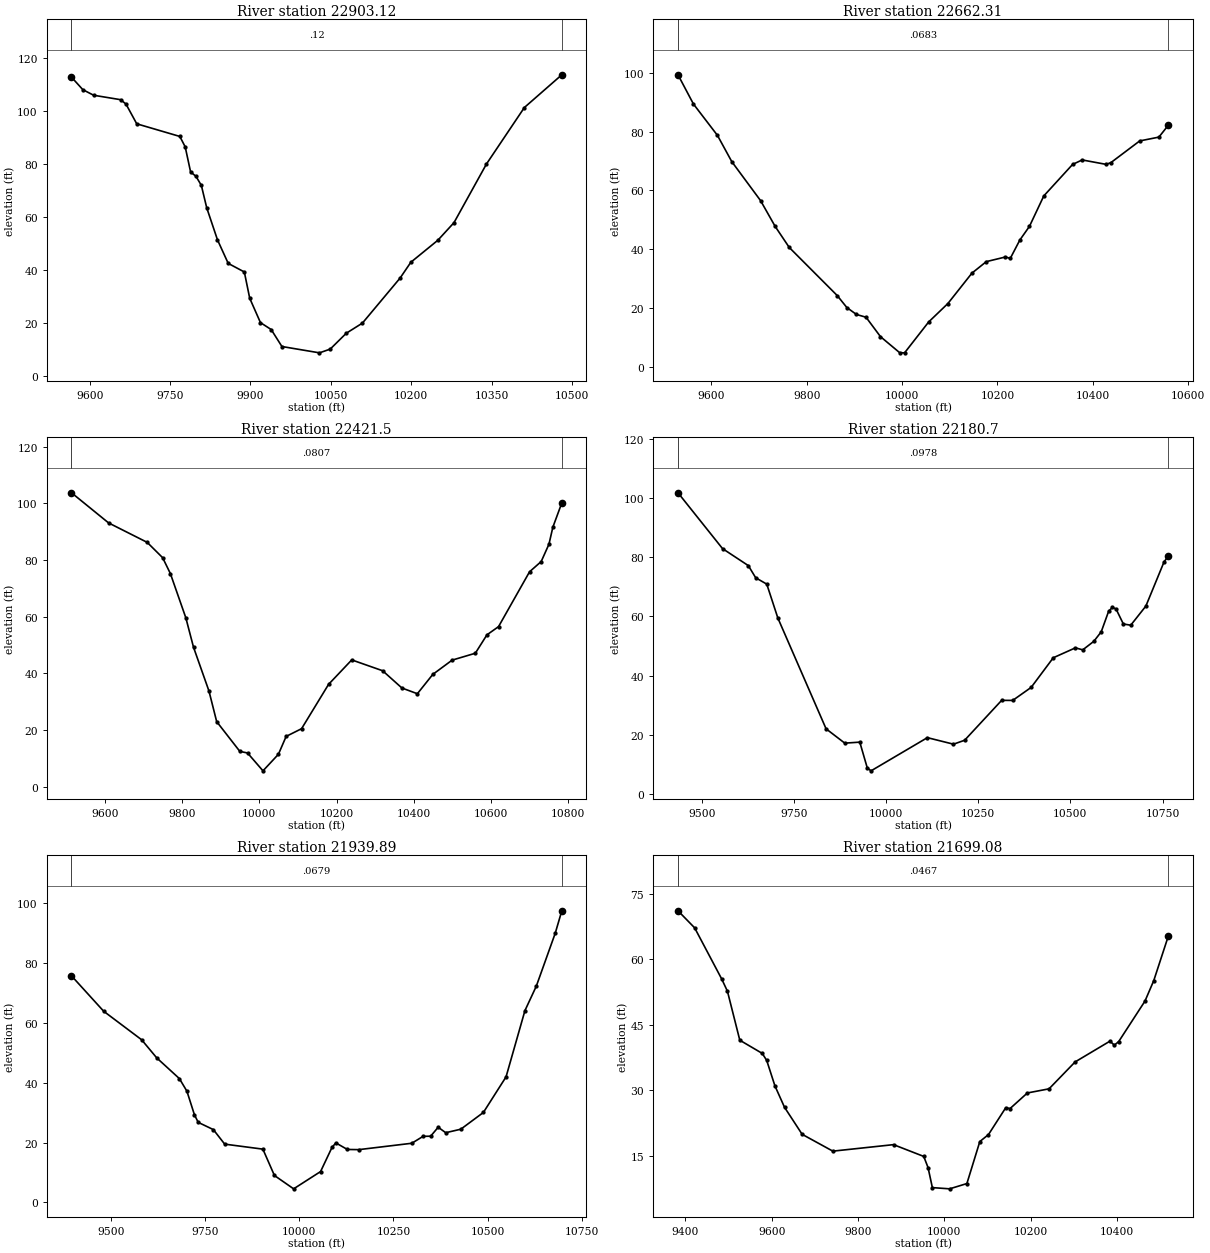
Type RM Length L Ch R = 1 ,22903.12,240.807000,240.807000,240.807000
XS GIS Cut Line= 6
869813.999965543850370.341631021870040.954534813850393.670766111
870333.998839507850410.140313789870451.520030941 850420.31336685
870644.260241359850445.044821639870723.926690339850458.225793128
#Sta/Elev= 30
9566.174112.81439587.315108.0874 9607.45105.98019657.743104.2993 9667.79102.6539
9687.88495.177399768.25890.402199778.30486.462369788.35176.990869798.38975.32168
9808.41571.903659818.44163.426029838.49251.319829858.54442.401189888.62139.16005
9898.64729.233229918.69820.010469938.71817.397929958.73610.97566 10028.88.586524
10048.839.99895910078.8616.0050810108.95 19.837710179.2136.8617510199.2842.83969
10249.6151.1497410279.8157.8249410340.3379.9873210411.05101.339410480.91113.7164
#Mann= 3 , 0 , 0
9566.174    0.12       09566.174    0.12       010480.91    0.12       0
#XS Ineff= 2 , 0
       0                               0
Bank Sta=9566.174,10480.91
Exp/Cntr=0.3,0.1

Type RM Length L Ch R = 1 ,22662.31,240.806900,240.806900,240.806900
XS GIS Cut Line= 6
869762.709956452850595.175180822870076.474596248850625.837998341
870164.295663359850636.354293073870284.203316419850654.044229064
870369.495414897850664.785068519870784.644976837850707.615483708
#Sta/Elev= 30
9530.02699.34593 9562.4789.385919612.70878.738089642.85169.780519703.137  56.536
9733.85547.722729763.42340.563189863.94324.209159884.08620.136249904.22917.77099
9924.37216.828199954.657 10.22039995.079 4.7392610005.194.70971510055.7415.22716
10096.0621.4999510146.4431.8372510176.5935.7527610216.7937.3376510226.8436.84701
10246.9443.1140210267.0447.7489110297.1858.1245110357.4868.8252110377.5870.36244
10427.8368.8558110437.88 69.450710498.2576.83087 10538.578.1315510558.26 82.1781
#Mann= 3 , 0 , 0
9530.026  0.0683       09530.026  0.0683       010558.26  0.0683       0
#XS Ineff= 2 , 0
       0                               0
Bank Sta=9530.026,10558.26
Exp/Cntr=0.3,0.1

Type RM Length L Ch R = 1 , 22421.5,240.806900,240.806900,240.806900
XS GIS Cut Line= 6
869709.013102464850870.990100726869969.355895213850881.159025972
870553.358055753850888.362828492 870663.40510788850892.048665385
870858.104870551850905.111474202870978.169250359850917.907351629
#Sta/Elev= 30
9513.113 103.7089609.24893.077239709.29386.21806 9749.3180.811119769.319 75.2235
9809.32459.641919829.325  49.2289869.328 33.79959889.32922.997799949.33312.50278
9969.33511.9369710009.345.64052610049.3411.4868910069.3417.7856710109.3520.50839
10179.3536.1503510239.3644.7646810319.3640.9441610369.3734.8523810409.3932.83737
10449.4239.6616410499.4744.6843810559.5747.1165310589.6653.6005110619.7556.50403
10700.0975.8399610730.2679.4564710750.3785.5593110760.4391.5383310783.73100.1465
#Mann= 3 , 0 , 0
9513.113  0.0807       09513.113  0.0807       010783.73  0.0807       0
#XS Ineff= 2 , 0
       0                 10171.8       0
Bank Sta=9513.113,10783.73
Exp/Cntr=0.3,0.1

Type RM Length L Ch R = 1 , 22180.7,240.807000,240.807000,240.807000
XS GIS Cut Line= 6
869664.515805452851161.446581427869954.979451364851165.570861549
870377.189897981851093.984186279870577.812811793851075.047489271
870776.979330212851074.810801873 870986.44676255851090.781385191
#Sta/Elev= 30
9435.422101.76219556.261 82.90099626.26777.155639646.28173.043889676.32570.90021
9706.36959.45046 9837.2422.016959887.91817.18251 9928.6817.518889949.0618.781287
9959.2517.82493610112.0419.0371910182.8716.8295910213.0918.1535810313.5131.63347
10343.5931.6182110393.6236.0143610453.6446.0269810513.6549.3728510533.6548.69985
10563.6751.58231 10583.754.7822810603.7461.7080110613.7563.0226710623.7762.54336
 10643.857.4275510663.8457.0293510704.8663.4885110754.25 78.439710765.7580.32851
#Mann= 3 , 0 , 0
9435.422  0.0978       09435.422  0.0978       010765.75  0.0978       0
#XS Ineff= 2 , 0
       0                10233.76       0
Bank Sta=9435.422,10765.75
Exp/Cntr=0.3,0.1

Type RM Length L Ch R = 1 ,21939.89,240.806900,240.806900,240.806900
XS GIS Cut Line= 6
869681.199258198851367.201857632869952.282961797851400.311379607
870095.574341542851391.250259885870415.063050568851331.070583365
870587.894471636851313.917997792870972.400397823851331.204133863
#Sta/Elev= 30
9395.50275.724649480.96363.88923 9581.7254.35948 9621.8348.301739681.86841.38827
 9701.8837.175579721.89229.270759731.89826.760449772.01624.346319802.16919.48785
9903.52117.815239934.1349.0139299985.1564.54998410056.6410.3227810087.1518.44427
 10097.319.8944810127.7617.7077210158.0717.6482810298.7819.7807110328.8222.09646
10348.83 22.140810368.8325.1337510388.8423.3071810428.8524.4736710488.8630.07624
10548.9841.9652210599.1364.1114410629.2872.2708710679.5489.9646610697.0397.46572
#Mann= 3 , 0 , 0
9395.502  0.0679       09395.502  0.0679       010697.03  0.0679       0
#XS Ineff= 2 , 0
       0                10226.09       0
Bank Sta=9395.502,10697.03
Exp/Cntr=0.3,0.1

Type RM Length L Ch R = 1 ,21699.08,240.807000,240.807000,240.807000
XS GIS Cut Line= 6
869708.510708275 851489.94510428869877.261908036851543.378027451
870064.223478384851582.989235372870215.945317908851595.115523322
870499.842741952851600.956679476870828.102822382851648.539754692
#Sta/Elev= 30
9382.91571.082499421.54667.173619484.33155.45553 9497.5552.666699526.18841.46667
9578.23838.448739588.54936.845829607.613 31.01879629.79426.127159670.69319.93725
9741.829 16.0856 9882.4717.573879952.50114.879869962.50112.331999972.5017.742459
 10012.57.46215510052.518.66994910082.5118.2839510102.5219.8701410142.5826.02448
 10152.625.8325710192.6929.3971910242.9230.3436310303.3436.4990710384.1641.25377
10394.2840.33729 10404.4 41.159310465.3350.4275510485.6655.1111410519.3865.28616
#Mann= 3 , 0 , 0
9382.915  0.0467       09382.915  0.0467       010519.38  0.0467       0
#XS Ineff= 2 , 0
       0                   10124       0
Bank Sta=9382.915,10519.38
Exp/Cntr=0.3,0.1

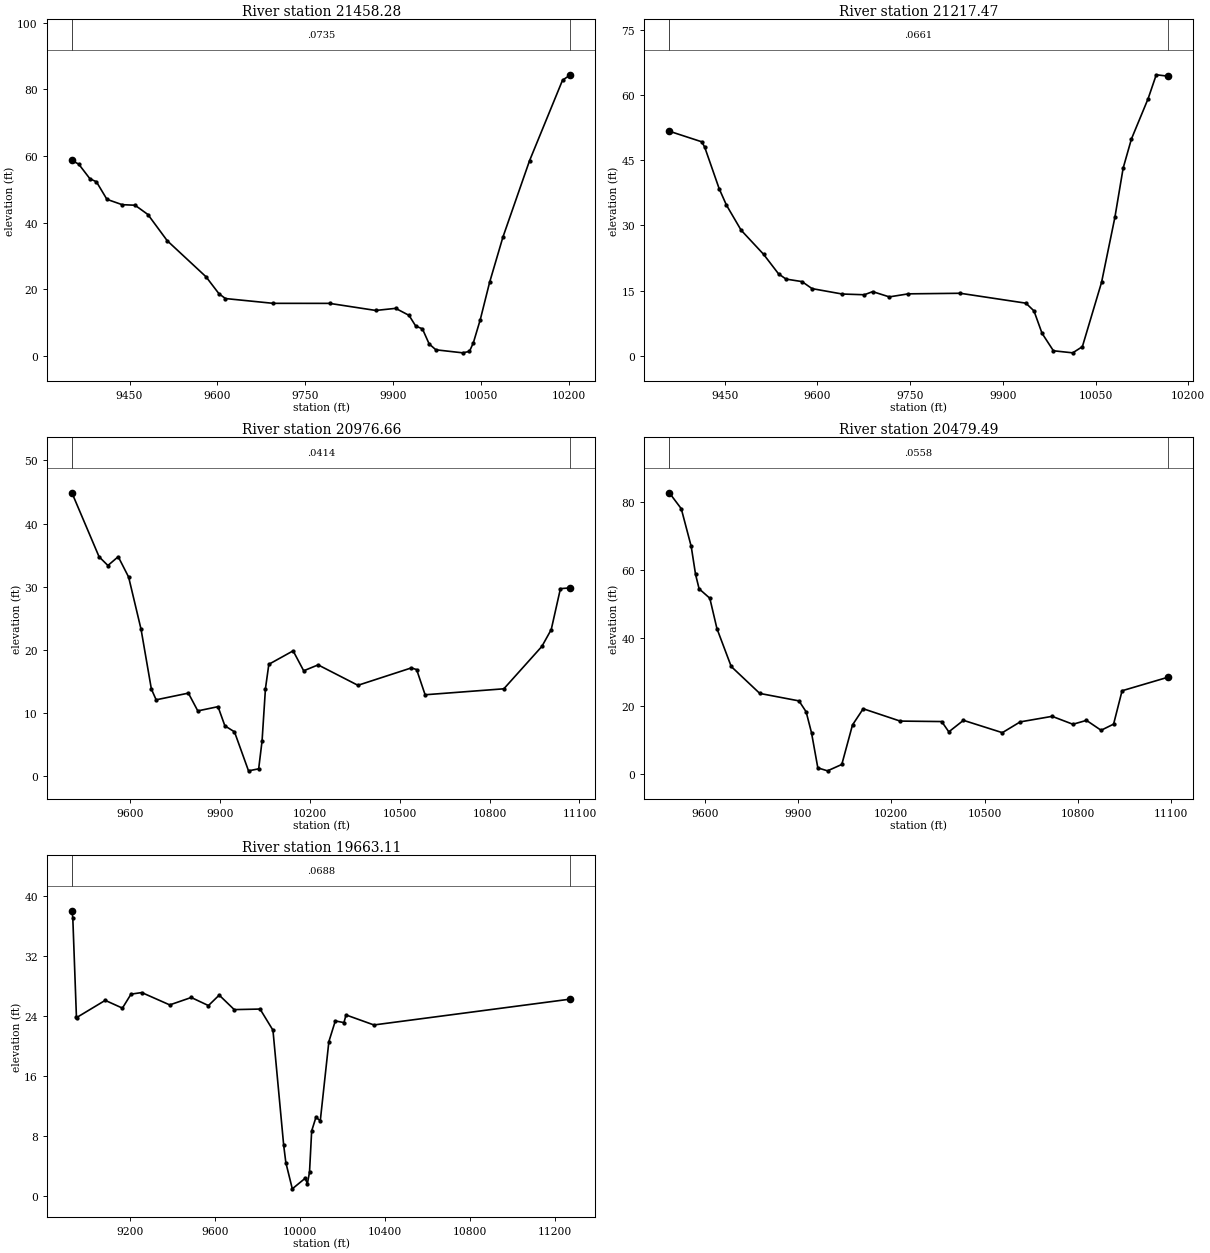
Type RM Length L Ch R = 1 ,21458.28,240.806900,240.806900,240.806900
XS GIS Cut Line= 6
869676.918323899851540.160162593869992.129073397851686.591133103
870093.962666783 851737.13154145870181.756392171 851783.62118042
870301.013283356851850.773651089870437.128559214851923.027150033
#Sta/Elev= 30
9351.53358.695679363.18457.582579382.40453.179339393.39852.298679411.33147.03134
9437.37145.428649459.35845.262649481.34442.478749514.32434.622439580.65423.79628
9602.76718.705889613.824 17.27459695.37315.840389791.61815.828739870.53913.70633
9904.486 14.33639927.31612.237839938.7829.0218219950.2488.1841329961.7143.667454
 9973.181.90357310019.11 0.99422 10030.61.43516410037.274.041774   1004910.93529
 10064.922.0932310087.6435.6621710133.1258.58407 10189.582.7497810203.1184.38271
#Mann= 3 , 0 , 0
9351.533  0.0735       09351.533  0.0735       010203.11  0.0735       0
#XS Ineff= 2 , 0
       09567.899                       0
Bank Sta=9351.533,10203.11
Exp/Cntr=0.3,0.1

Type RM Length L Ch R = 1 ,21217.47,240.806900,240.806900,240.806900
XS GIS Cut Line= 6
869616.230229494851587.526426115869783.835622373851695.697621601
869869.938957926851762.815749232869930.893114711851817.708362032
870028.693319381851921.608068273870206.846412922852128.523458814
#Sta/Elev= 30
 9360.4251.72872 9412.91 49.28759417.65648.067759441.12838.467939452.86434.69686
9476.60828.916719512.93423.359979537.151 18.8534 9549.2617.64776 9575.0917.06632
9591.35515.449379640.15314.203639675.94214.034859689.39914.755179716.31413.54545
9747.11214.24378 9831.0914.377149937.36612.093079950.38710.312679963.407 5.15792
9981.8081.12444210013.060.64864310028.672.072027 10059.716.8907310081.2831.87271
10094.64 43.218510108.0149.9278710135.06 59.2374 10148.264.73375   1016764.41976
#Mann= 3 , 0 , 0
 9360.42  0.0661       0 9360.42  0.0661       0   10167  0.0661       0
#XS Ineff= 2 , 0
       09580.313                       0
Bank Sta=9360.42,10167
Exp/Cntr=0.3,0.1

Type RM Length L Ch R = 1 ,20976.66,497.173300,497.173300,497.173300
XS GIS Cut Line= 6
869534.974600823851676.447798314869759.969446725851904.150407346
 869980.88153913852284.766473523870133.966172449852486.549875963
870352.920471983852702.399701861  870622.4189259852912.495131389
#Sta/Elev= 30
9405.30744.866679495.97234.741459525.49533.356659559.96134.750769594.69531.52228
9636.15623.26875 9670.6113.805849686.55812.09885 9794.1713.15685  9825.610.34374
9893.14411.013139916.0157.981788 9948.117.0276859994.927 0.8567310028.85 1.17476
10040.165.57196410051.4813.87061 10062.817.7200610143.8819.8484410179.1316.69277
10227.3217.6258910360.1814.3955910538.5117.1466410556.2316.8857110584.5512.89671
10847.4213.8412610974.3620.5482311005.6423.21712 11036.329.6903911069.89 29.8223
#Mann= 3 , 0 , 0
9405.307  0.0414       09405.307  0.0414       011069.89  0.0414       0
#XS Ineff= 2 , 0
       0                10153.43       0
Bank Sta=9405.307,11069.89
Exp/Cntr=0.3,0.1

Type RM Length L Ch R = 1 ,20479.49,816.382000,816.382000,816.382000
XS GIS Cut Line= 3
869031.447878313852140.372009621870084.280094452852733.670576521
870435.961812195852915.059847208
#Sta/Elev= 30
9485.74982.639669524.26277.951519556.28366.842369570.176 58.65289581.655 54.3849
 9616.0951.614939639.04742.674699684.96131.533499776.78923.612769903.05321.41109
 9926.01 18.20099943.29612.048919963.6651.7063669994.8810.83486910040.792.716603
10075.2314.3463910109.6719.1000110228.4615.4724410362.1915.3347610385.1512.30416
10432.1515.6959410557.3312.0647110614.7215.2351110717.5616.86813 10784.414.53693
10828.0415.6799210875.0812.76709 10915.314.5782110942.5924.3952411089.9528.36526
#Mann= 3 , 0 , 0
9485.749  0.0558       09485.749  0.0558       011089.95  0.0558       0
#XS Ineff= 2 , 0
       09817.768        10331.92       0
Bank Sta=9485.749,11089.95
Exp/Cntr=0.3,0.1

Type RM Length L Ch R = 1 ,19663.11,181.173500,181.173500,181.173500
XS GIS Cut Line= 5
867946.633777894 853182.56497055867976.229036314853203.960331871
869198.099643498853019.234377354869659.425644377852961.975359131
870266.910576366852949.301504322
#Sta/Elev= 30
8926.95337.999498931.10937.074018948.17823.855198949.61623.756259083.592 26.0452
9164.50125.011389204.95626.875729255.52427.086159387.00125.438589488.13826.42832
9569.04725.350599619.61526.74629 9690.41 24.81159811.77424.885049872.45622.06378
9923.0246.6782659933.1384.3846939963.4790.89447510024.162.30866710034.271.571904
10044.393.115591 10054.58.61809410074.7310.4484110094.969.96502310135.4120.54073
10165.7523.3020210206.1823.0768210216.2624.0977410347.2522.7632111271.7126.21408
#Mann= 3 , 0 , 0
8926.953  0.0688       08926.953  0.0688       011271.71  0.0688       0
#XS Ineff= 2 , 0
       0 9827.38        10168.08       0
Bank Sta=8926.953,11271.71
Exp/Cntr=0.3,0.1