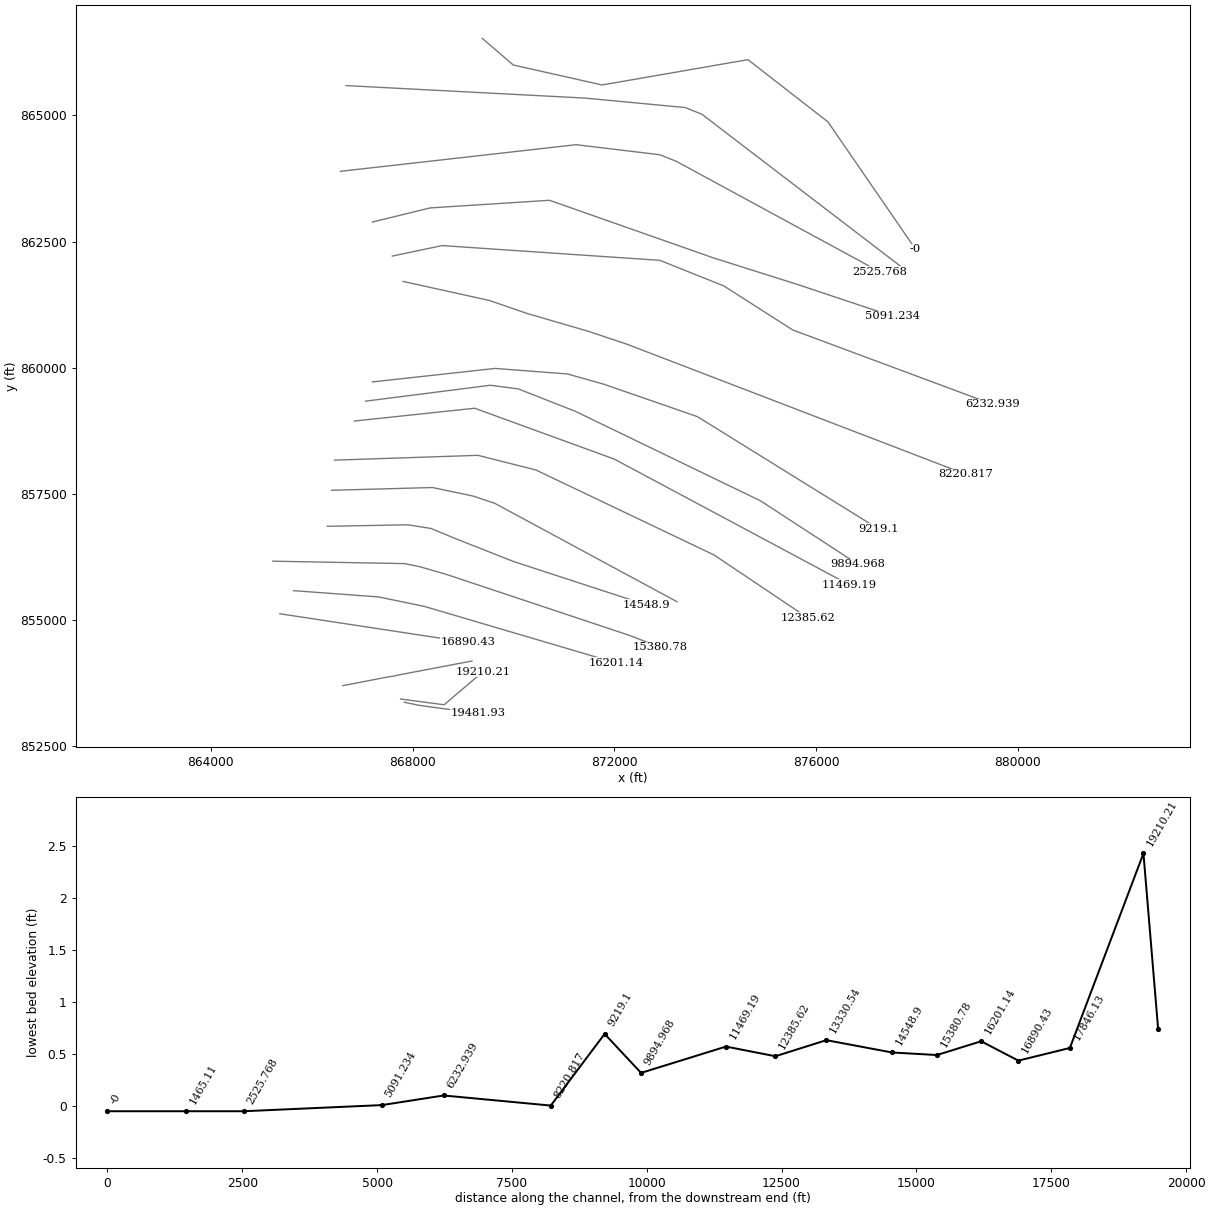
HEC-RAS study 16857_ras.prj: 16857

--- 16857_ras.g01 (geometry) --- (continued)

Type RM Length L Ch R = 3 , 19587.3,,,
BEGIN DESCRIPTION:
END DESCRIPTION:
Bridge Culvert--1,0,-1,-1, 0
Deck Dist Width WeirC Skew NumUp NumDn MinLoCord MaxHiCord MaxSubmerge Is_Ogee
43.586750,94.000000,2.6,0, 53, 53, , , 0.95, 0, 0,0,,
 9023.35 9040.81 9050.93 9061.04 9071.16 9111.63 9141.98 9162.21 9192.56 9222.91
 9233.02 9243.14 9253.26 9263.37 9293.72 9303.84 9344.31 9354.42 9364.54 9374.65
 9415.12 9435.35 9465.70 9496.05 9506.17 9526.40 9556.75 9587.10 9597.22 9607.33
 9617.45 9627.57 9637.68 9647.80 9657.92 9688.26 9698.38 9708.50 9718.61 9728.73
 9748.96 9769.20 9789.43 9799.55 9819.78 9829.90 9870.73 9870.7310126.7310126.73
10173.8610194.0910228.62
   23.66   23.73   23.87   23.77   23.87   23.95   24.17   24.17   24.34   24.21
   24.08   24.16   24.12   24.39   24.35   24.48   24.36   24.53   24.36   24.32
   24.36   24.43   24.69   24.59   24.92   24.67   25.10   25.02   24.22   25.22
   25.47   25.50   25.18   24.98   24.90   25.06   24.96   25.22   25.34   25.13
   25.04   25.22   25.54   25.36   25.36   25.15   25.13   25.13   24.99   24.99
   24.91   24.96   24.50
 -976.34 -976.27 -976.13 -976.23 -976.13 -976.05 -975.83 -975.83 -975.66 -975.79
 -975.92 -975.84 -975.88 -975.61 -975.65 -975.52 -975.64 -975.47 -975.64 -975.68
 -975.64 -975.57 -975.31 -975.41 -975.08 -975.33 -974.90 -974.98 -975.78 -974.78
 -974.53 -974.50 -974.82 -975.02 -975.10 -974.94 -975.04 -974.78 -974.66 -974.87
 -974.96 -974.78 -974.46 -974.64 -974.64 -974.85 -974.87   20.13   19.99 -975.01
 -975.09 -975.04 -975.50
 9023.35 9040.81 9050.93 9061.04 9071.16 9111.63 9141.98 9162.21 9192.56 9222.91
 9233.02 9243.14 9253.26 9263.37 9293.72 9303.84 9344.31 9354.42 9364.54 9374.65
 9415.12 9435.35 9465.70 9496.05 9506.17 9526.40 9556.75 9587.10 9597.22 9607.33
 9617.45 9627.57 9637.68 9647.80 9657.92 9688.26 9698.38 9708.50 9718.61 9728.73
 9748.96 9769.20 9789.43 9799.55 9819.78 9829.90 9878.69 9878.6910134.6910134.69
10173.8610194.0910228.62
   23.66   23.73   23.87   23.77   23.87   23.95   24.17   24.17   24.34   24.21
   24.08   24.16   24.12   24.39   24.35   24.48   24.36   24.53   24.36   24.32
   24.36   24.43   24.69   24.59   24.92   24.67   25.10   25.02   24.22   25.22
   25.47   25.50   25.18   24.98   24.90   25.06   24.96   25.22   25.34   25.13
   25.04   25.22   25.54   25.36   25.36   25.15   25.12   25.12   24.99   24.99
   24.91   24.96   24.50
 -976.34 -976.27 -976.13 -976.23 -976.13 -976.05 -975.83 -975.83 -975.66 -975.79
 -975.92 -975.84 -975.88 -975.61 -975.65 -975.52 -975.64 -975.47 -975.64 -975.68
 -975.64 -975.57 -975.31 -975.41 -975.08 -975.33 -974.90 -974.98 -975.78 -974.78
 -974.53 -974.50 -974.82 -975.02 -975.10 -974.94 -975.04 -974.78 -974.66 -974.87
 -974.96 -974.78 -974.46 -974.64 -974.64 -974.85 -974.88   20.12   19.99 -975.01
 -975.09 -975.04 -975.50
Pier Skew, UpSta & Num, DnSta & Num=  ,9955.40, 2 ,9963.35, 2 , 0 , 0 , 0 ,,
    4.00    4.00
 -974.92   25.08
    4.00    4.00
 -974.92   25.08
Pier Skew, UpSta & Num, DnSta & Num=  ,10042.07, 2 ,10050.02, 2 , 0 , 0 , 0 ,,
    4.00    4.00
 -974.96   25.04
    4.00    4.00
 -974.97   25.03
BR Coef=-1 , 0 , 0 ,, 0 ,,,0.8,0,1,0,
WSPro=,,,, 1 ,,,, 0 ,,,, 0 ,,,,-1 ,-1 ,-1 , 0 , 0 , 0 , 0 , 0
BC Design=,, 0 ,, 0 ,,,,,,

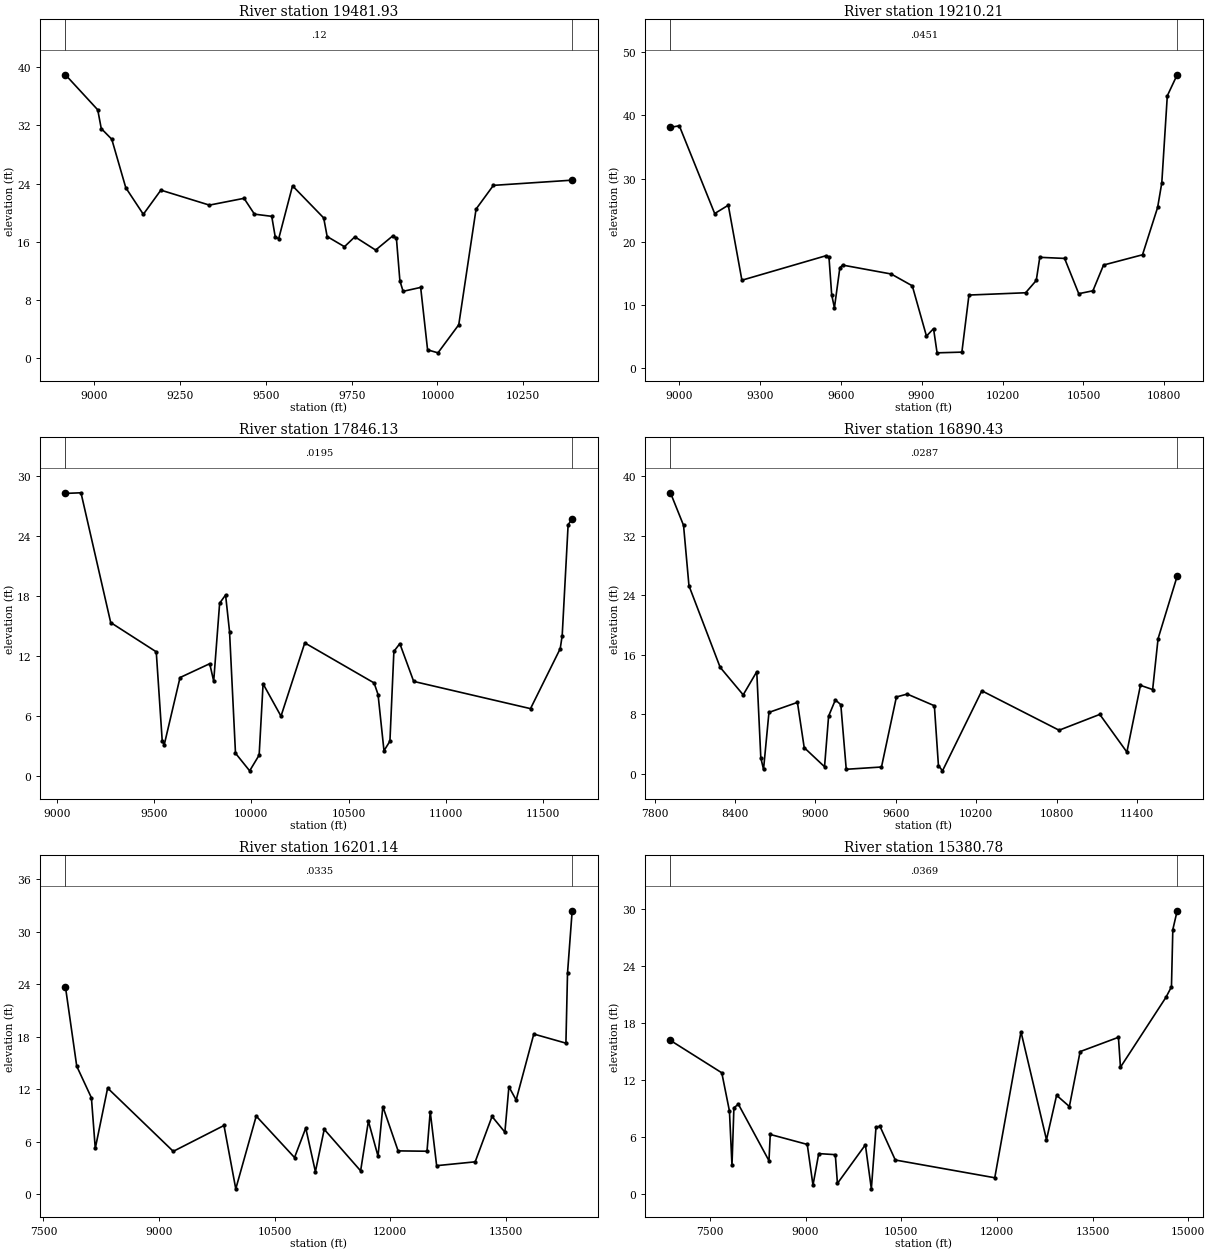
Type RM Length L Ch R = 1 ,19481.93,271.723700,271.723700,271.723700
XS GIS Cut Line= 3
867832.881635833 853369.33912245868115.840469047 853309.56735669
 869292.45330564853147.931882945
#Sta/Elev= 30
8915.63838.97122 9009.7934.15196 9020.01 31.57959050.67230.110389091.55523.43972
9142.65819.789349193.76223.111799335.21421.054329436.15321.987379466.435 19.8127
9516.90419.510949526.99816.708589537.09216.420369577.46823.705069668.31319.29192
9678.40716.735089728.87715.335659759.15816.697759819.72214.874659870.19116.84388
9880.28516.480579890.37910.659529899.7029.2015649950.943 9.739959971.1311.155387
10001.410.74521210061.984.60586310112.4520.5118910162.92  23.768 10392.524.48418
#Mann= 3 , 0 , 0
8915.638    0.12       08915.638    0.12       0 10392.5    0.12       0
#XS Ineff= 2 , 0
       0 9852.58        10162.81       0
Bank Sta=8915.638,10392.5
Exp/Cntr=0.3,0.1

Type RM Length L Ch R = 1 ,19210.21,1364.075000,1364.075000,1364.075000
XS GIS Cut Line= 3
867762.471605002853432.871869851868624.576184486853318.213010748
869392.887457618853971.969761373
#Sta/Elev= 30
 8969.0538.116629001.86438.372589133.00924.477839183.44925.79538 9233.8913.92288
9546.61917.811619556.70717.572929566.79611.602249576.8849.558017 9597.0615.89619
9607.14816.319739787.26614.908189865.56213.035739918.0835.0791959944.344 6.25721
9957.4742.42761310049.392.54013410075.6511.5743510285.7311.9377810325.1213.88245
10338.2517.5470310430.1617.3727310482.6811.79028 10535.212.25063 10574.616.32509
10719.0317.9488110775.0825.4460210790.51 29.337110810.9443.1121910847.5646.44233
#Mann= 3 , 0 , 0
 8969.05  0.0451       0 8969.05  0.0451       010847.56  0.0451       0
#XS Ineff= 2 , 0
       0 9848.41        10136.23       0
Bank Sta=8969.05,10847.56
Exp/Cntr=0.3,0.1

Type RM Length L Ch R = 1 ,17846.13,955.703800,955.703800,955.703800
XS GIS Cut Line= 6
866616.511480782853697.821702119867490.447257008 853865.89676187
867569.456143513853878.595529863867647.381713123853891.341649501
867720.216529068853908.831692277869175.376013224854185.858308203
#Sta/Elev= 30
9044.25328.22769 9124.1828.290959276.92915.347189511.14412.428969541.6943.580674
9551.877 3.137329633.3439.8629119786.09211.245149806.4589.5000669837.00817.27897
9867.55818.097859887.92414.448229918.4742.3180579991.3630.55937810040.112.130908
10060.389.23516210152.456.01013510274.7613.3198810631.059.32593210651.41 8.17158
10681.94 2.5624910712.483.51790310732.8412.4721710763.3813.2460610834.64  9.4785
11435.23 6.7623411587.9312.7433711598.1114.0403611628.6525.1107611649.3925.67371
#Mann= 3 , 0 , 0
9044.253  0.0195       09044.253  0.0195       011649.39  0.0195       0
#XS Ineff= 2 , 0
       09869.601        10885.16       0
Bank Sta=9044.253,11649.39
Exp/Cntr=0.3,0.1

Type RM Length L Ch R = 1 ,16890.43,689.287800,689.287800,689.287800
XS GIS Cut Line= 2
865368.496609828855122.516785066 869105.94955722854554.214309299
#Sta/Elev= 30
 7918.5737.748338016.18233.378948056.64225.274658289.28614.32943 8461.2410.63464
8562.38913.738198592.7342.1775368612.9640.6376848653.4248.2794378865.8389.622883
8916.4123.5504579068.1370.9880789098.4817.7791399149.0569.9627579189.5169.309191
9229.9760.6458939492.9640.9521119604.229  10.3539685.14810.738399887.4479.172389
9917.7921.1499359948.1370.43775210241.4711.1778210818.025.88739811121.478.009642
11323.772.95222211424.9211.9120111515.9511.3452811556.4118.1716311698.9826.56328
#Mann= 3 , 0 , 0
 7918.57  0.0287       0 7918.57  0.0287       011698.98  0.0287       0
#XS Ineff= 2 , 0
       0  9781.9        10958.78       0
Bank Sta=7918.57,11698.98
Exp/Cntr=0.3,0.1

Type RM Length L Ch R = 1 ,16201.14,820.367700,820.367700,820.367700
XS GIS Cut Line= 4
 865638.67424292855580.463366559867325.323199156855456.624805159
868241.174264175855266.271023043872032.864853607854147.940078416
#Sta/Elev= 30
7785.27823.718727931.99814.646348122.50911.035078172.6445.2484018333.07412.14454
9185.3624.9094899843.8317.8671449997.0360.62363310262.598.94327510759.934.203513
 10905.97.57563811031.012.58469411145.697.42836711618.252.68099311719.128.363872
11844.234.35879111906.7810.0285412104.874.96466412480.214.92330212521.919.457238
12605.323.27293313105.76 3.71243 13324.78.89911713491.527.10285113543.6512.29177
13637.4810.7850113866.8518.3223314283.8817.2814614304.7625.2820614365.0632.41686
#Mann= 3 , 0 , 0
7785.278  0.0335       07785.278  0.0335       014365.06  0.0335       0
#XS Ineff= 2 , 0
       09141.918        11006.07       0
Bank Sta=7785.278,14365.06
Exp/Cntr=0.3,0.1

Type RM Length L Ch R = 1 ,15380.78,831.873300,831.873300,831.873300
XS GIS Cut Line= 6
865230.221540396856164.838615432867841.910685406 856116.31284825
868140.825204689 856055.88034859 868666.65629129855904.063361352
872298.139227581854693.944353685872908.743010627854458.491565507
#Sta/Elev= 30
 6880.7916.140277685.70812.728337805.7298.7040857845.7352.9537057875.7419.034962
7945.7539.4182768425.8363.4549128445.8396.2273189025.9395.1760769115.9550.876371
 9205.974.2078839466.0154.0944319499.5551.0643979937.5485.13250910031.220.491499
10104.086.98109510166.537.086727 10406.73.53125911966.711.65978412377.7917.05502
12777.875.67464112936.4410.3563913136.719.17345113305.3614.9637513906.1816.47292
 13937.8 13.314414651.9320.6943514737.6821.7985314759.1127.8339814827.4329.81448
#Mann= 3 , 0 , 0
 6880.79  0.0369       0 6880.79  0.0369       014827.43  0.0369       0
#XS Ineff= 2 , 0
       0 8417.89        11452.41       0
Bank Sta=6880.79,14827.43
Exp/Cntr=0.3,0.1

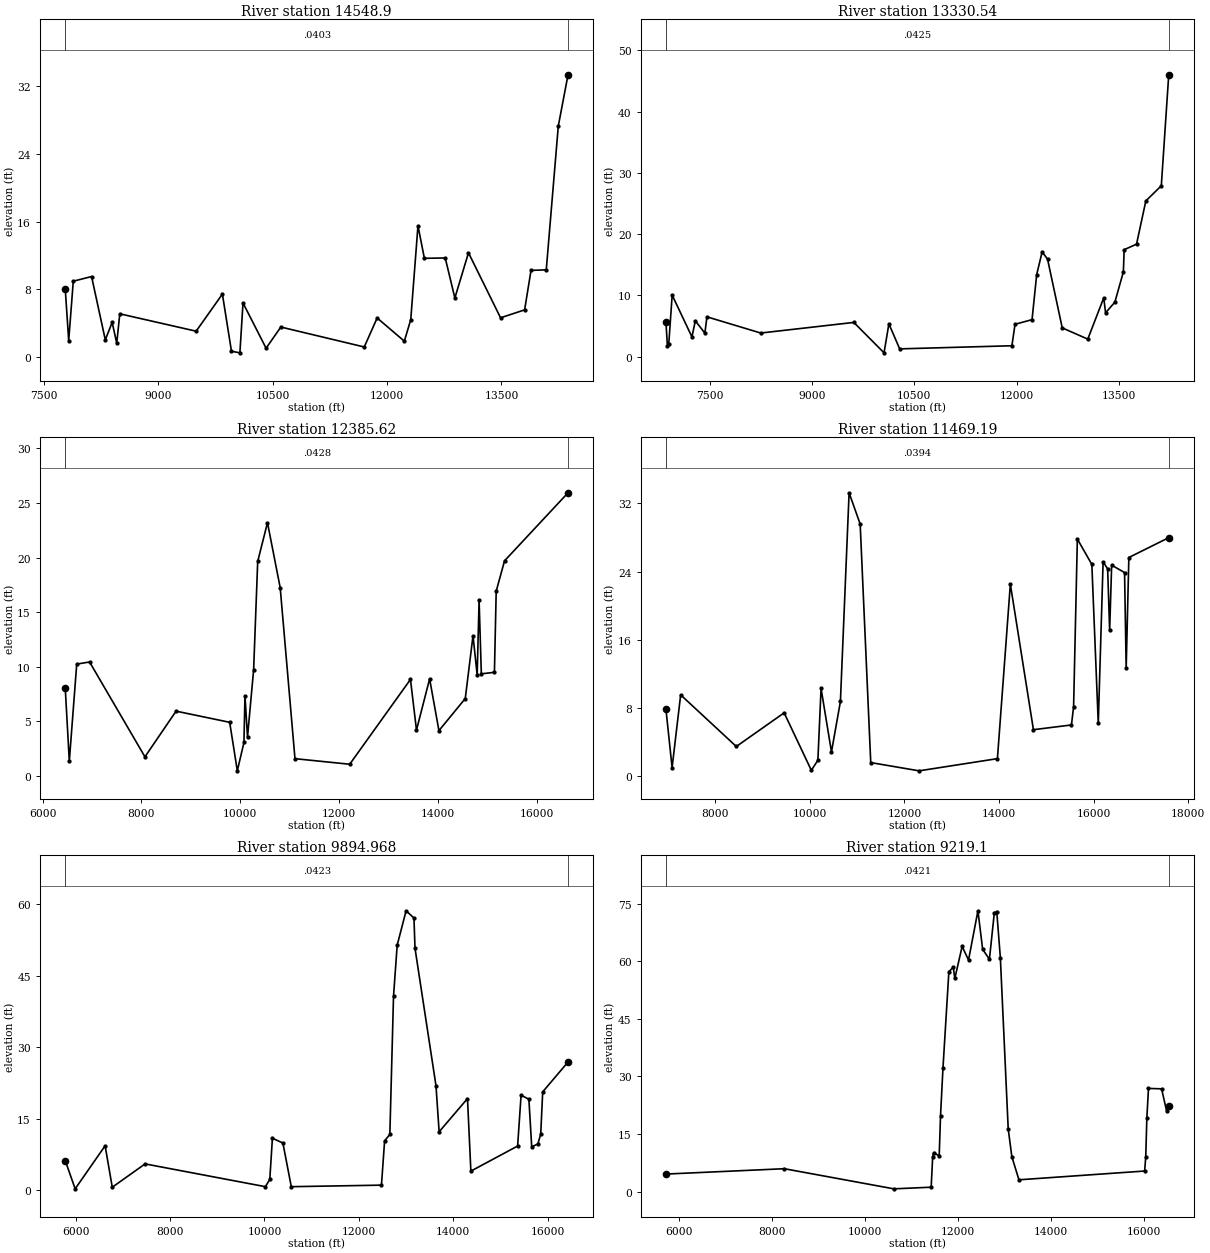
Type RM Length L Ch R = 1 , 14548.9,1218.362400,1218.362400,1218.362400
XS GIS Cut Line= 6
866309.582314902856856.528878352867904.167640405856886.026541868
868361.742890099856813.839364312868893.974797544856594.475227879
870007.891211512856155.924572394872636.602855142855298.257848191
#Sta/Elev= 30
7777.4538.0644337822.8781.9504957882.8888.9716988122.9299.523217 8302.962.050405
8392.9764.1088378452.9861.6530428492.9935.1221079494.6373.0707829839.0687.449739
9958.0450.70447710068.680.51604510109.476.40501110412.311.06367410605.763.562097
11699.981.20704911869.254.63072912225.921.89199912310.074.43664912404.7415.51608
12488.8911.6723112762.3711.71762 12888.6 6.9895413067.42 12.325613488.174.651145
13803.745.58839713887.8910.2507214087.7410.3112614245.5327.2839814373.4433.34008
#Mann= 3 , 0 , 0
7777.453  0.0403       07777.453  0.0403       014373.44  0.0403       0
#XS Ineff= 2 , 0
       08036.431        12283.79       0
Bank Sta=7777.453,14373.44
Exp/Cntr=0.3,0.1

Type RM Length L Ch R = 1 ,13330.54,944.916100,944.916100,944.916100
XS GIS Cut Line= 5
866393.609824463857570.184703785868396.112994983857624.813810072
869200.096378706857455.506936377 869633.19660275857309.533086049
873240.957130991855361.601567908
#Sta/Elev= 30
6853.1055.6894326874.5031.710732 6894.512.0609876944.52910.047957234.6373.238174
7284.6565.8627097424.708 3.845357454.7196.5094688245.0133.8661099611.446 5.59697
10055.270.63420410126.365.360093 10284.81.28148811932.651.79009911978.115.291754
12228.136.04944712296.3213.4002612375.8717.0910412455.4215.9433312671.354.707748
13046.372.87315513280.739.60416513307.767.17173213444.138.89791213569.1413.85372
13580.5117.4642513762.3418.3637613898.7125.41827   1412627.8908814235.0546.00044
#Mann= 3 , 0 , 0
6853.105  0.0425       06853.105  0.0425       014235.05  0.0425       0
#XS Ineff= 2 , 0
       07129.561        12210.82       0
Bank Sta=6853.105,14235.05
Exp/Cntr=0.3,0.1

Type RM Length L Ch R = 1 ,12385.62,916.428900,916.428900,916.428900
XS GIS Cut Line= 5
866452.728439459858167.616438284869295.237288119858263.094516462
870445.709827087857972.113324955873974.134167819856288.683996433
875832.523405218855041.909084187
#Sta/Elev= 30
6457.0968.0538266539.4131.3675926689.498 10.25086949.64510.443838070.2761.762168
8700.6325.9427649785.7634.9217889940.4860.47988210074.583.07587710095.217.356669
10146.783.57200410270.569.74064410353.0819.6461910550.8723.1942610808.4417.24376
11107.591.59354212215.581.08265613445.448.84706613567.324.20807913833.238.899628
14021.594.15895114554.93 7.0996114711.4812.8459914795.77  9.264314834.7416.09312
14880.07 9.3609315144.999.49585915181.1216.9299115349.71 19.702816635.2225.93151
#Mann= 3 , 0 , 0
6457.096  0.0428       06457.096  0.0428       016635.22  0.0428       0
#XS Ineff= 2 , 0
       06857.643        13037.34       0
Bank Sta=6457.096,16635.22
Exp/Cntr=0.3,0.1

Type RM Length L Ch R = 1 ,11469.19,1574.226600,1574.226600,1574.226600
XS GIS Cut Line= 4
866845.679582741858942.905349561869230.303794358859196.571763849
871998.528508471858188.239460398876658.422031633855695.936147825
#Sta/Elev= 30
 6959.347.821315 7089.39 0.952867270.4069.5019258447.007 3.434019458.2017.389771
10032.910.63337710171.261.81528210238.5510.2622310458.622.794217 10647.68.727454
10831.1133.2525911065.2629.5743611288.751.54339812310.440.57261813966.612.007115
14239.9422.5113414727.625.40761415531.595.96480615576.958.10723615656.3427.81825
15962.5324.8316916098.616.14349416200.6825.1372916296.6724.3030516339.0817.08842
16381.4824.74406 16654.323.8766516688.3212.6541116745.0225.6458517588.0927.97491
#Mann= 3 , 0 , 0
 6959.34  0.0394       0 6959.34  0.0394       017588.09  0.0394       0
#XS Ineff= 2 , 0
       07475.015        13694.14       0
Bank Sta=6959.34,17588.09
Exp/Cntr=0.3,0.1

Type RM Length L Ch R = 1 ,9894.968,675.868000,675.868000,675.868000
XS GIS Cut Line= 6
867066.850667639859336.771943514869537.770759789859652.161668493
 870094.20570246859580.322555529 871224.92343974859136.232305255
874897.478249828857360.726095031876830.059448264856101.970951247
#Sta/Elev= 30
5780.3366.2444595990.1740.3199666625.285 9.342166776.5020.657491  7472.1 5.54257
10020.780.770671   101142.29185610169.5310.9170510391.689.917616 10569.40.769582
12479.861.094013 12546.510.3696712657.5711.7051612735.3240.6531212813.0851.36483
 13001.958.5636913168.5157.0444713190.7250.6997913635.0221.9311613701.6612.26868
14302.5519.2236114374.154.03290215364.689.28367115437.8919.9282115603.37 19.0965
15663.049.12139715794.319.72406415853.9811.7984515895.9520.6288616432.8626.88883
#Mann= 3 , 0 , 0
5780.336  0.0423       05780.336  0.0423       016432.86  0.0423       0
#XS Ineff= 2 , 0
       06333.222        12109.38       0
Bank Sta=5780.336,16432.86
Exp/Cntr=0.3,0.1

Type RM Length L Ch R = 1 ,  9219.1,998.282500,998.282500,998.282500
XS GIS Cut Line= 6
867201.542039485859718.064100752869636.557798304 859985.73133216
871070.663711726859875.907719487871788.219290205859673.586421257
873644.397293565 859030.84214411877235.513872106856803.678308128
#Sta/Elev= 30
5713.9154.5457868262.3285.94032810619.180.69420211423.451.119243 11455.28.951162
11476.3610.1491111596.139.25798811624.5219.6353411677.4332.1642611804.4257.29031
11899.67 58.4699 11932.355.5273512090.1563.8911512227.7260.3355312430.1373.17521
12531.5463.1416312677.2360.5276412783.1472.6656612835.1172.9657512912.5860.98802
13081.7716.3310813159.689.09014313312.653.04940716019.075.33784116042.619.074879
16066.1419.0970816101.4426.8732516383.8526.7608716489.7521.0715916537.4322.30487
#Mann= 3 , 0 , 0
5713.915  0.0421       05713.915  0.0421       016537.43  0.0421       0
#XS Ineff= 2 , 0
       06372.035        11583.46       0
Bank Sta=5713.915,16537.43
Exp/Cntr=0.3,0.1

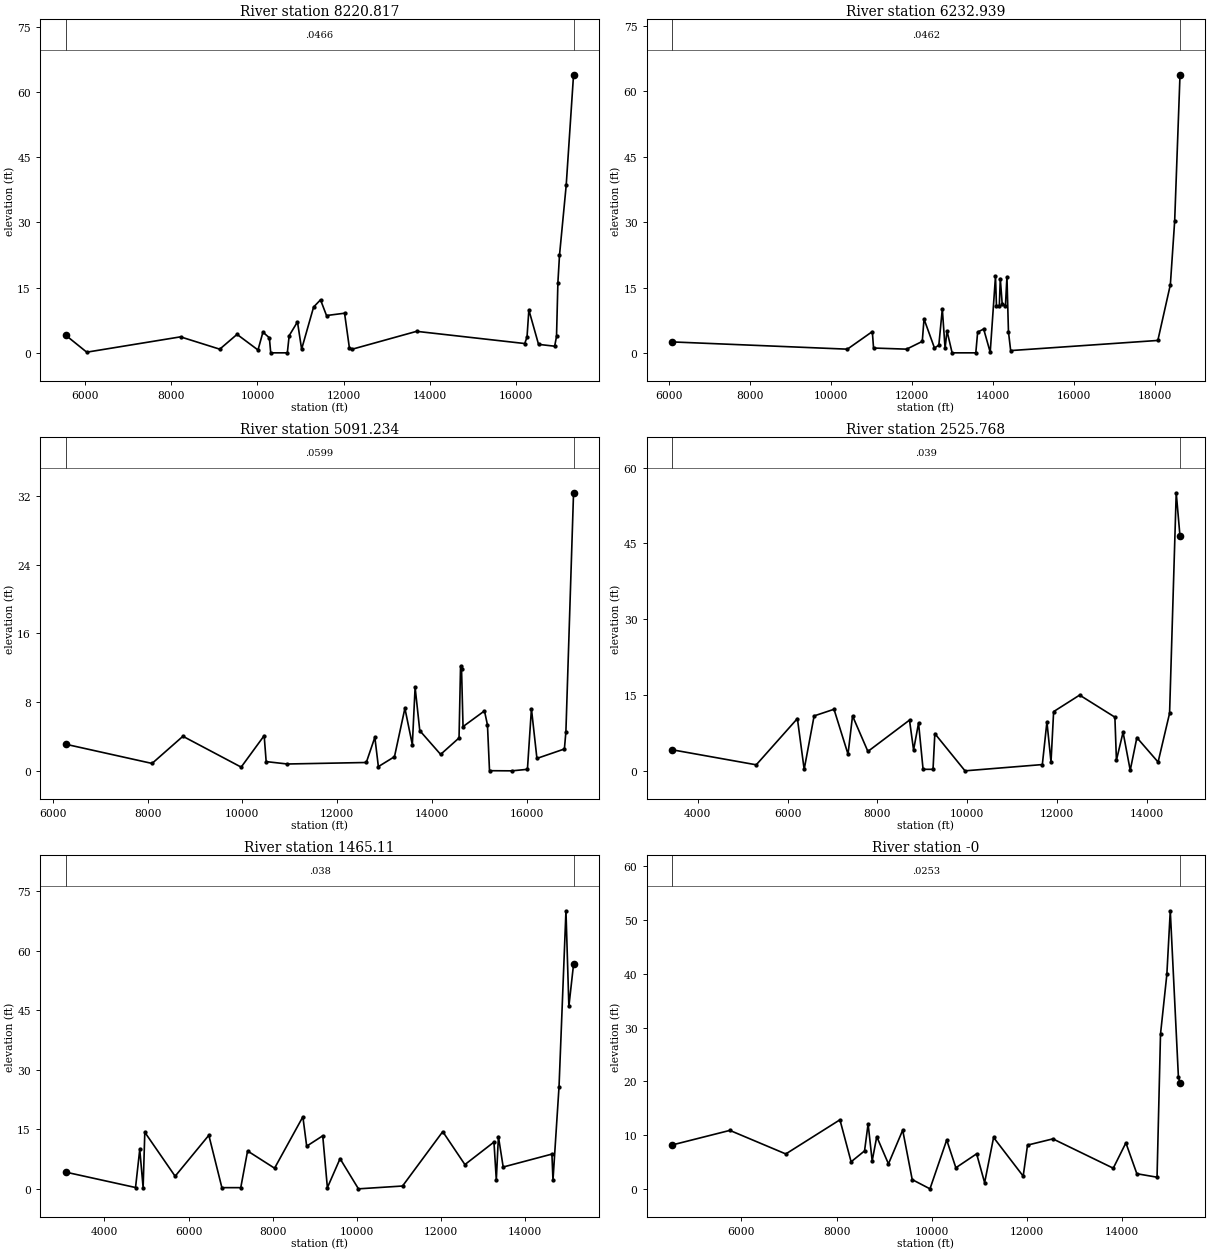
Type RM Length L Ch R = 1 ,8220.817,1987.878500,1987.878500,1987.878500
XS GIS Cut Line= 6
867812.891239689861710.282605717869521.492751378861333.277188382
870266.793649778861076.477394973871494.735599976860718.429046737
872252.253118517860464.646421958878964.513948429857887.994152456
#Sta/Elev= 30
5538.9154.096994 6032.620.158239 8211.48 3.684439123.3960.8481279525.3194.255587
10012.310.66083310126.924.76582510276.213.46679610308.350.00623410693.960.006234
10736.81 3.9620210929.627.12900311026.020.86068511304.5210.5438211465.1912.20529
11604.448.58796812024.01 9.1226612135.631.16891812204.28 0.8503813698.244.952667
16210.372.14714216263.933.61451916306.789.87551816531.721.95758516906.621.529608
16949.47 3.76962 16981.616.1619617018.7822.4453517174.4138.5502517345.27 63.9813
#Mann= 3 , 0 , 0
5538.915  0.0466       05538.915  0.0466       017345.27  0.0466       0
#XS Ineff= 2 , 0
       06676.795        11407.76       0
Bank Sta=5538.915,17345.27
Exp/Cntr=0.3,0.1

Type RM Length L Ch R = 1 ,6232.939,1141.704600,1141.704600,1141.704600
XS GIS Cut Line= 6
867597.261824877862212.833149149868585.312900906862420.877952049
  872901.7684387862128.348758329874170.346177439861620.823097429
875535.924740663860747.968754017879498.667531267859273.635210802
#Sta/Elev= 30
6061.3292.60693810397.230.94359611014.19 4.9681111044.531.20390211861.220.946529
12248.962.71831612292.057.84969712550.54 1.2157812658.251.84814912744.4110.14534
12812.841.13368412860.315.13056912986.770.10301813572.410.10301813618.08 4.85055
13766.625.55640113928.450.23523614059.0117.6514514082.7410.9031914153.9510.90319
14177.6917.1013814225.1611.2326514305.0910.9031914342.2217.5409714379.364.943852
14434.110.61987918072.472.94155518381.8915.7175318488.5830.3172618620.5363.77821
#Mann= 3 , 0 , 0
6061.329  0.0462       06061.329  0.0462       018620.53  0.0462       0
#XS Ineff= 2 , 0
       08020.847        12685.83       0
Bank Sta=6061.329,18620.53
Exp/Cntr=0.3,0.1

Type RM Length L Ch R = 1 ,5091.234,2565.466300,2565.466300,2565.466300
XS GIS Cut Line= 6
867203.640879302862887.183540614868345.931087222863167.395736066
870714.258120564863318.676357324873959.126517498862178.041934887
875661.302713463  861639.9860683877508.026415434861022.988716687
#Sta/Elev= 30
6268.4733.1136138095.0220.8715898746.3474.0335079975.5440.44355310460.764.106364
10503.231.08518610949.18 0.8077912616.160.98177112796.67 3.9136412870.990.502592
13210.761.65496913430.947.29283913587.693.051095 13646.39.74043113744.774.690729
14184.821.92378514573.413.84045414605.1412.1591914626.1711.8475214657.715.161513
15110.016.98900315173.27 5.3555415216.370.027059 15689.90.01082716016.740.187714
16101.097.24209516217.06 1.4560316796.952.55523216828.584.57162716989.9232.38033
#Mann= 3 , 0 , 0
6268.473  0.0599       06268.473  0.0599       016989.92  0.0599       0
#XS Ineff= 2 , 0
       09329.982        13586.62       0
Bank Sta=6268.473,16989.92
Exp/Cntr=0.3,0.1

Type RM Length L Ch R = 1 ,2525.768,1060.658000,1060.658000,1060.658000
XS GIS Cut Line= 5
866570.124467481863893.097746175871241.939400711864420.687621032
872900.773722106864221.589728407873230.797093617864089.636043815
877259.171029402861902.148756959
#Sta/Elev= 30
3425.5254.1320075302.2541.1450116218.03810.310316368.9920.251157 6590.39 10.8342
7033.18712.148787345.1583.2585157445.79310.831787787.9543.7952668714.28110.00328
8804.9274.0824858915.7169.4211499016.4340.2537819238.0130.250984  9278.37.326478
9950.203-0.0482311671.711.19378911773.849.66024111864.871.68494911923.1811.68789
12502.1114.9584413287.2710.5860913321.412.06012613469.347.59891313628.650.063991
13776.586.53737714249.231.68864514504.8511.3592714652.7855.0423714737.1846.38829
#Mann= 3 , 0 , 0
3425.525   0.039       03425.525   0.039       014737.18   0.039       0
#XS Ineff= 2 , 0
       08584.936        11867.43       0
Bank Sta=3425.525,14737.18
Exp/Cntr=0.3,0.1

Type RM Length L Ch R = 1 , 1465.11,1465.109900,1465.109900,1465.109900
XS GIS Cut Line= 5
866682.270682225865592.229461251871417.653936154865345.000000034
873404.289964872865156.919909361873734.309535992865024.970775847
877693.334684466861995.320824752
#Sta/Elev= 30
3075.6494.1764954740.6430.2856734840.7799.8840554920.8880.2509844960.94214.21604
5681.9233.1297396483.01313.461446793.4350.2509847242.0850.2509847404.2669.500703
8045.8445.154191 8718.8418.118338809.24310.707259190.94213.322129301.4340.250984
9602.7757.55635310039.93-0.0482311088.510.66332212044.2314.3746512570.786.066475
13261.8911.7412413317.322.18880613367.68 13.142913481.015.45150814639.49 8.71156
14664.672.12615514808.64 25.722114973.1970.0464715042.4345.9262215153.6756.55352
#Mann= 3 , 0 , 0
3075.649   0.038       03075.649   0.038       015153.67   0.038       0
#XS Ineff= 2 , 0
       09156.005        12097.97       0
Bank Sta=3075.649,15153.67
Exp/Cntr=0.3,0.1

Type RM Length L Ch R = 1 ,      -0,0.000000,0.000000,0.000000
XS GIS Cut Line= 6
869380.594240616866529.159873959869995.356606479866000.557986943
 871757.41787815865604.796785828874647.103449153866106.558804568
876232.651081669864873.634732903877971.112462244862346.883324752
#Sta/Elev= 30
 4538.668.1159365756.56510.837836933.2486.4509358072.11212.812628307.4054.989474
8590.0357.0201228664.94812.048788750.5635.152511 8846.889.6725089093.0234.600804
9392.67610.88179 9592.861.6723579966.374-0.0482310318.769.04883810511.033.877861
10948.036.474422 11116.21.09574411304.729.51888811927.362.31867712018.948.097304
12552.069.257812 13822.33.79642314088.118.51458314318.742.76694614743.58 2.11764
14816.4128.7695614949.9339.8910715021.9851.74688 15192.720.8541615226.8319.62352
#Mann= 3 , 0 , 0
 4538.66  0.0253       0 4538.66  0.0253       015226.83  0.0253       0
#XS Ineff= 2 , 0
       08684.978        12257.24       0
Bank Sta=4538.66,15226.83
Exp/Cntr=0.3,0.1